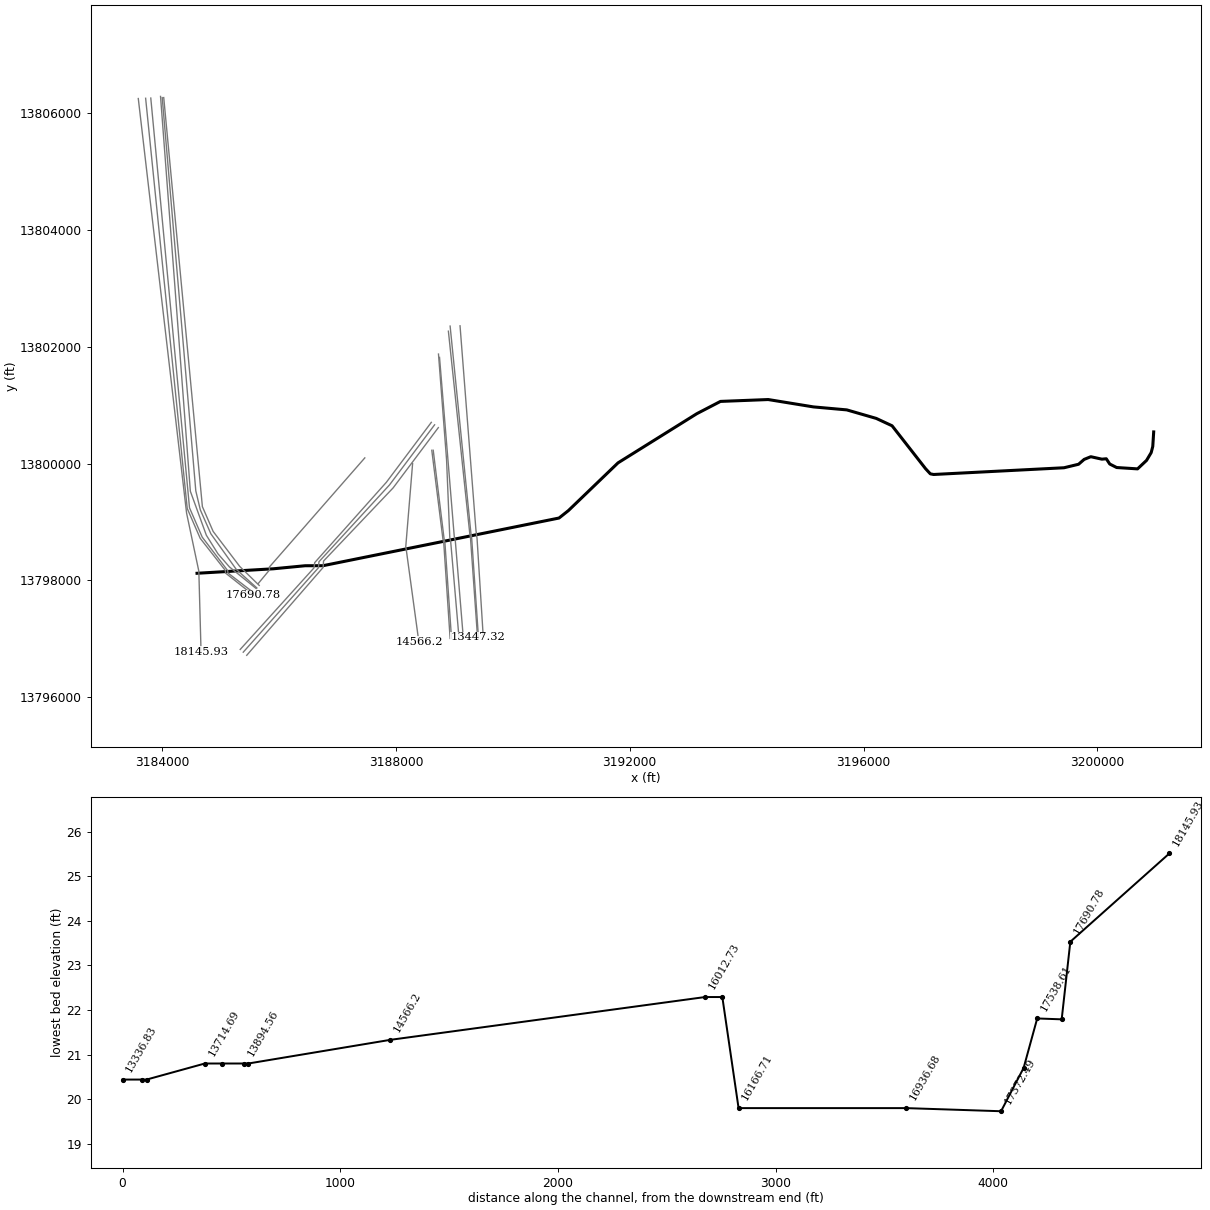
--- B113-00-00.prj (project) ---

Proj Title=B113-00-00
Current Plan=p02
Default Exp/Contr=.3,.1
English Units
Geom File=g01
Flow File=f01
Flow File=f02
Plan File=p01
Plan File=p02
Y Axis Title=Elevation
X Axis Title(PF)=Main Channel Distance
X Axis Title(XS)=Station
BEGIN DESCRIPTION:
HCFCD MODEL SUMMARY METADATA
The purpose of this summary is to document the high points of hydrologic and hydraulic models filed within the HCFCD Model and Map Management (M3) system.  The document includes references to the project that prompted the creation or update of the model.
DESCRIPTION OF PROJECT:
The following model was the hydraulic model which represented the effective condition of Harris County's watersheds.
PURPOSE OF PROJECT:
Development of effective models to support the National Flood Insurance Program.
HCFCD Watershed Unit ID: B
M3 Study Identifier: 2007_Effective_B
Engineer: HCFCD
Project Name: EffectiveFEMA Study for watershed Armand Bayou (B)
Study Completion Date: 6/18/2007
FEMA Case Number: [No Data]
FEMA Approval Date: [No Date in Database]
Vertical Datum: NAVD 1988
Datum Note: 2001 ADJ
HYDRAULICS
HCFCD Unit No.:  B113-00-00
Hydraulic Program Name: HEC-RAS
Hydraulic Program Version: 3.0.1
Steady Hydraulic Model: Yes
Unsteady Hydraulic Model: No
Update 1: The effective FEMA hydraulic model for unit number B113-00-00 has been updated by FEMA LOMR 14-06-4559P with an effective date of 10/16/2015.
Update 2: The effective FEMA hydraulic model for unit number B113-00-00 has been updated by FEMA LOMR 16-06-1957PP with an effective date of 04/27/2017.
END DESCRIPTION:
DSS File=dss
DSS Export Rating Curves= 0
DSS Export Rating Curve Sorted= 0
DSS Export Volume Flow Curves= 0
DXF OffsetX= 0
DXF OffsetY= 0
DXF ScaleX= 1
DXF ScaleY= 10

--- B113-00-00.p02 (plan) ---

Plan Title=FEMA Effective Floodway 2017
Version=Version 3.0.1  May 2012
Short Identifier=Eff+LOMR_FW
Geom File=g01
Flow File=f02
Subcritical Flow
K Sum by GR= 0
Std Step Tol= 0.01
Critical Tol= 0.01
Num of Std Step Trials= 20
Max Error Tol= 0.3
Flow Tol Ratio= 0.001
Split Flow NTrial= 30
Split Flow Tol= 0.02
Split Flow Ratio= 0.02
Log Output Level= 0
Friction Slope Method= 0
Unsteady Friction Slope Method= 2
Secant Critical Depth
Global Vel Dist= 0 , 0 , 0
Global Log Level= 0
CheckData=True
Encroach Param=-1 ,0,0, 2
Encroach River=B113-00-00
Encroach Reach=B113-00-00_0011
Encroach Node=18145.93
       110631.0810890.01
Encroach Node=17690.78
       1 6249.77 6333.49
Encroach Node=17651.05
       1 6246.42 6335.88
Encroach Node=17594.83
       1 6216.42 6365.88
Encroach Node=17538.61
       1 6208.33  6387.7
Encroach Node=17476.12
       1 6161.73 6332.59
Encroach Node=17424.31
       1 6161.73 6332.59
Encroach Node=17372.49
       1 6240.04 6362.31
Encroach Node=16936.68
       1 1691.89 1821.53
Encroach Node=16551.7
       1 1691.89 1821.53
Encroach Node=16166.71
       1 3503.11 3585.57
Encroach Node=16129.39
       1 3503.11 5050.42
Encroach Node=16092.06
       1    4995 5050.42
Encroach Node=16012.73
       1    4992 5050.42
Encroach Node=14566.2
       1 4975.29 5024.71
Encroach Node=13914.56
       1  4969.3  5030.7
Encroach Node=13894.56
       1  4969.3  5030.7
Encroach Node=13844.29
       1  4969.3  5030.7
Encroach Node=13794.01
       1  4969.3  5030.7
Encroach Node=13714.69
       1  4969.3  5030.7
Encroach Node=13447.32
       1 4966.61 5033.39
Encroach Node=13427.32
       1 4966.61 5033.39
Encroach Node=13382.1
       1 4966.61 5033.39
Encroach Node=13336.83
       1 4966.61 5033.39
Encroach Node=13249.3
       1 4966.61 5033.39
Encroach Node=11996.49
       1    4952 5023.53
Encroach Node=11976.48
       1    4960 5028.53
Encroach Node=11941
       1    4960 5028.53
Encroach Node=11904.77
       1    4980 5048.53
Encroach Node=11820.67
       1    4985    5054
Encroach Node=11535.7
       1    4961  5038.5
Encroach Node=11515.83
       1    4961 5038.29
Encroach Node=11373.45
       1    4960 5038.29
Encroach Node=11231.07
       14970.4975045.504
Encroach Node=11119.59
       14968.497 5028.09
Encroach Node=10576.76
       14962.496    5037
Encroach Node=9630.347
       1    4968    5029
Encroach Node=8857.144
       1 4973.09 5062.51
Encroach Node=8817.757
       1 4965.05 5034.96
Encroach Node=8704.11
       1 4965.05 5034.96
Encroach Node=8590.454
       1    4967 5036.91
Encroach Node=8414.412
       1 4973.09    5035
Encroach Node=7185.976
       1  4972.6  5027.4
Encroach Node=6312.18
       1 4970.47 5029.53
Encroach Node=5471.81
       1 4982.55 5037.45
Encroach Node=4359.305
       1 4980.15    5048
Encroach Node=4318.915
       1 4970.15 5029.85
Encroach Node=4227
       1 4970.15 5029.85
Encroach Node=4135.178
       1 4970.15 5029.85
Encroach Node=3975.095
       1 4970.15 5029.85
Encroach Node=3355.123
       1 4972.23 5027.77
Encroach Node=3335.121
       1 4971.85 5027.39
Encroach Node=3274.7
       1 4971.85 5027.39
Encroach Node=3214.266
       1 4962.23 5017.77
Encroach Node=3136.485
       1 4967.23 5022.77
Encroach Node=2312.536
       1 4972.84 5027.16
Encroach Node=1094.73
       1 4973.69 5026.31
BEGIN DESCRIPTION:
FEMA Effective Floodway June 2007 + LOMR 14-06-4559P + LOMR 16-06-1957P
END DESCRIPTION:
Computation Interval=1HOUR
Output Interval=1HOUR
Run HTab= 0
Run UNet= 0
Run PostProcess= 0
UNET Theta= 1
UNET ZTol= 0.02
UNET ZSATol= 0.1
UNET MxIter= 20
UNET MaxInSteps= 20
UNET DtIC= 0
UNET DtMin= 0
UNET MaxCRTS= 20
UNET WFStab= 2
UNET SFStab= 1
UNET WFX= 1
UNET SFX= 1
UNET Convert EG Bridges=-1
UNET Use Existing IB Tables=-1
Instantaneous Interval=1HOUR
DSS File=dss
Write IC File= 0
IC Time=0
Write Velocity= 0
Write Detailed= 0

--- B113-00-00.p01 (plan) ---

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Plan Title=FEMA Effective Multi-Profile 2017
Short Identifier=Eff+LOMR MP
Geom File=g01
Flow File=f01
FEMA Effective Multi-Profile June 2007 + LOMR 14-06-4559P + LOMR 16-06-1957P

--- B113-00-00.f02 (steady flow) ---

Flow Title=Effective Floodway 2017
Program Version=4.10
Number of Profiles= 2
Profile Names=1PCT_100yr, 1PCTFloodway_100yrFW
River Rch & RM=B113-00-00,B113-00-00_0011 ,18145.93
     323     323
River Rch & RM=B113-00-00,B113-00-00_0011 ,17690.78
     333     333
River Rch & RM=B113-00-00,B113-00-00_0011 ,17651.05
     641     641
River Rch & RM=B113-00-00,B113-00-00_0011 ,16936.68
     728     728
River Rch & RM=B113-00-00,B113-00-00_0011 ,14566.2
     786     786
River Rch & RM=B113-00-00,B113-00-00_0011 ,13914.56
     823     823
River Rch & RM=B113-00-00,B113-00-00_0011 ,13447.32
     843     843
River Rch & RM=B113-00-00,B113-00-00_0011 ,11996.49
     910     910
River Rch & RM=B113-00-00,B113-00-00_0011 ,11535.7
     945     945
River Rch & RM=B113-00-00,B113-00-00_0011 ,10576.76
     972     972
River Rch & RM=B113-00-00,B113-00-00_0011 ,9630.347
    1022    1022
River Rch & RM=B113-00-00,B113-00-00_0011 ,8857.144
    1091    1091
River Rch & RM=B113-00-00,B113-00-00_0011 ,7185.976
    1164    1164
River Rch & RM=B113-00-00,B113-00-00_0011 ,6312.18
    1220    1220
River Rch & RM=B113-00-00,B113-00-00_0011 ,5471.81
    1275    1275
River Rch & RM=B113-00-00,B113-00-00_0011 ,4359.305
    1381    1381
River Rch & RM=B113-00-00,B113-00-00_0011 ,3355.123
    1444    1444
River Rch & RM=B113-00-00,B113-00-00_0011 ,2312.536
    1509    1509
River Rch & RM=B113-00-00,B113-00-00_0011 ,1094.73
    1609    1609
Boundary for River Rch & Prof#=B113-00-00,B113-00-00_0011 , 1
Up Type= 0
Dn Type= 3
Dn Slope=0.0013
Boundary for River Rch & Prof#=B113-00-00,B113-00-00_0011 , 2
Up Type= 0
Dn Type= 3
Dn Slope=0.0013
DSS Import GetInterval= 0
DSS Import GetPeak= 0
DSS Import FillOption= 0

--- B113-00-00.f01 (steady flow) ---

Flow Title=Effective Multi-Profile 2017
Program Version=4.10
Number of Profiles= 4
Profile Names=10PCT_10yr, 2PCT_50yr, 1PCT_100yr, 0.2PCT_500yr
River Rch & RM=B113-00-00,B113-00-00_0011 ,18145.93
     185     276     323     463
River Rch & RM=B113-00-00,B113-00-00_0011 ,17690.78
     191     284     333     478
River Rch & RM=B113-00-00,B113-00-00_0011 ,17651.05
     367     548     641     921
River Rch & RM=B113-00-00,B113-00-00_0011 ,16936.68
     417     621     728    1039
River Rch & RM=B113-00-00,B113-00-00_0011 ,14566.2
     451     671     786    1114
River Rch & RM=B113-00-00,B113-00-00_0011 ,13914.56
     473     702     823    1160
River Rch & RM=B113-00-00,B113-00-00_0011 ,13447.32
     485     719     843    1186
River Rch & RM=B113-00-00,B113-00-00_0011 ,11996.49
     524     776     910    1269
River Rch & RM=B113-00-00,B113-00-00_0011 ,11535.7
     544     805     945    1313
River Rch & RM=B113-00-00,B113-00-00_0011 ,10576.76
     560     829     972    1347
River Rch & RM=B113-00-00,B113-00-00_0011 ,9630.347
     590     871    1022    1409
River Rch & RM=B113-00-00,B113-00-00_0011 ,8857.144
     630     929    1091    1493
River Rch & RM=B113-00-00,B113-00-00_0011 ,7185.976
     673     992    1164    1583
River Rch & RM=B113-00-00,B113-00-00_0011 ,6312.18
     706    1039    1220    1651
River Rch & RM=B113-00-00,B113-00-00_0011 ,5471.81
     739    1086    1275    1718
River Rch & RM=B113-00-00,B113-00-00_0011 ,4359.305
     801    1175    1381    1845
River Rch & RM=B113-00-00,B113-00-00_0011 ,3355.123
     838    1229    1444    1920
River Rch & RM=B113-00-00,B113-00-00_0011 ,2312.536
     876    1284    1509    1997
River Rch & RM=B113-00-00,B113-00-00_0011 ,1094.73
     936    1369    1609    2117
Boundary for River Rch & Prof#=B113-00-00,B113-00-00_0011 , 1
Up Type= 0
Dn Type= 3
Dn Slope=0.0013
Boundary for River Rch & Prof#=B113-00-00,B113-00-00_0011 , 2
Up Type= 0
Dn Type= 3
Dn Slope=0.0013
Boundary for River Rch & Prof#=B113-00-00,B113-00-00_0011 , 3
Up Type= 0
Dn Type= 3
Dn Slope=0.0013
Boundary for River Rch & Prof#=B113-00-00,B113-00-00_0011 , 4
Up Type= 0
Dn Type= 3
Dn Slope=0.0013
DSS Import GetInterval= 0
DSS Import GetPeak= 0
DSS Import FillOption= 0

--- B113-00-00.g01 (geometry) ---

Geom Title=B113-00-00
Program Version=4.10

River Reach=B113-00-00      ,B113-00-00_0011
Reach XY= 30
      3184598.25       13798123.        3185906.       13798200.
      3186448.25       13798252.     3186752.156    13798252.539
      3190790.75       13799068.      3190950.75       13799195.
        3191800.       13800012.      3193147.75       13800853.
      3193552.25       13801063.      3194368.75       13801095.
        3195143.       13800969.      3195712.75       13800918.
      3196217.75       13800772.        3196488.       13800646.
        3197061.       13799912.       3197142.5       13799824.
      3197199.25       13799813.      3199428.75       13799928.
       3199678.5       13799988.       3199773.5       13800071.
       3199887.5       13800117.       3200077.5       13800075.
      3200152.25       13800082.       3200211.5       13799992.
      3200329.75       13799932.      3200687.25       13799909.
        3200841.       13800054.      3200920.25       13800187.
       3200947.5       13800293.      3200963.25       13800541.

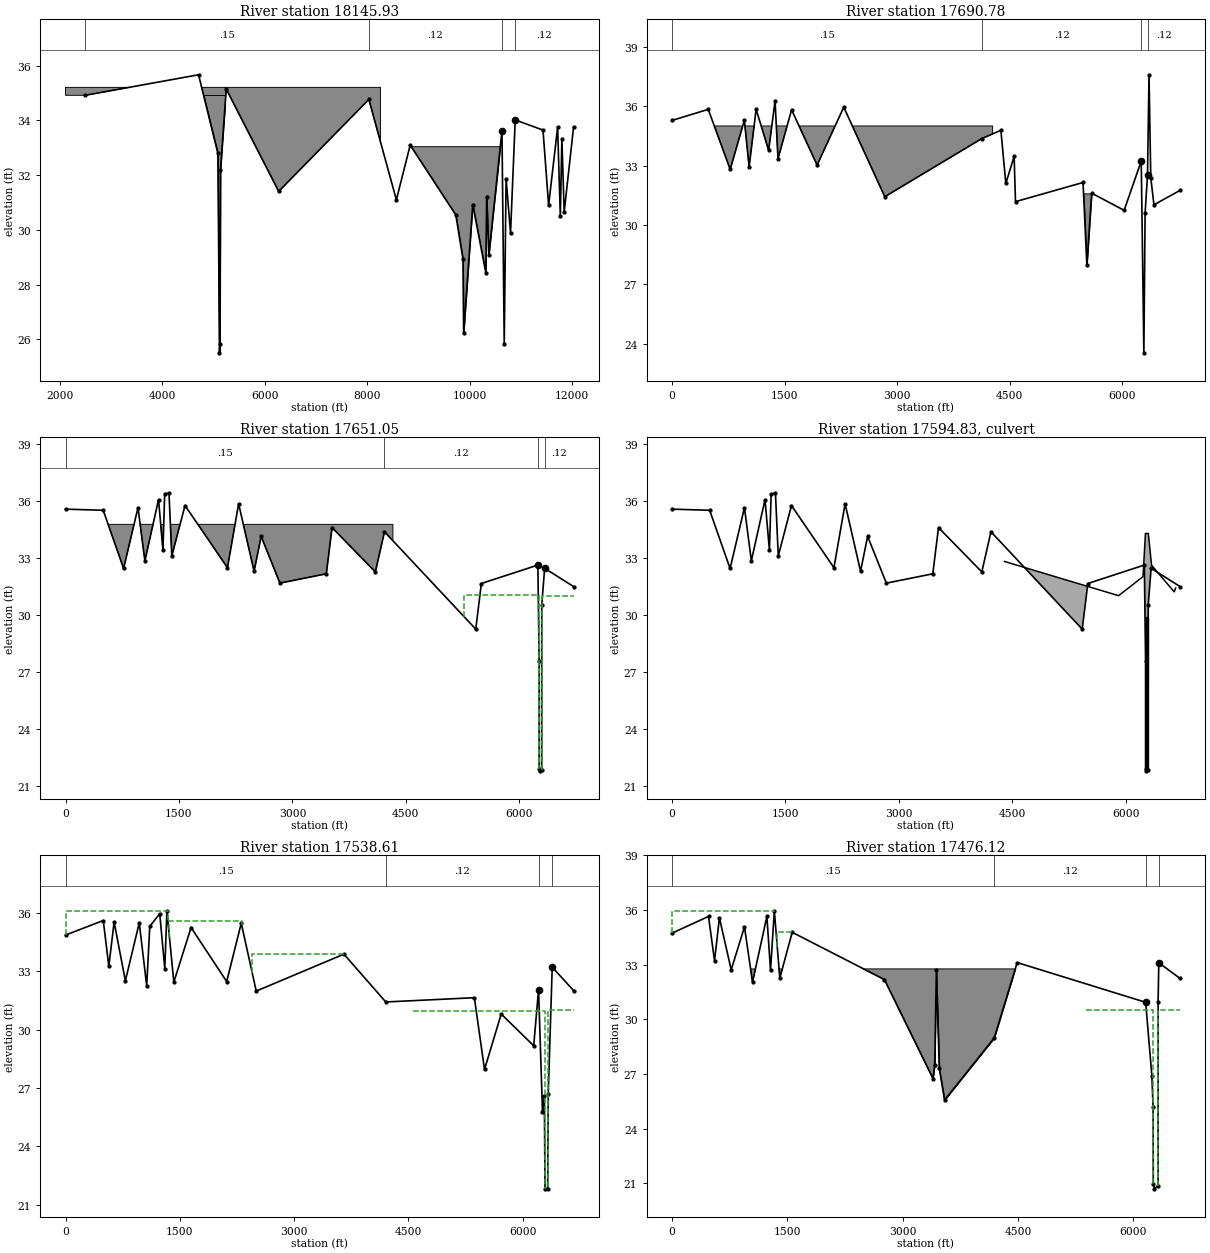
Type RM Length L Ch R = 1 ,18145.93,407.8,455.14,542.25
XS GIS Cut Line= 6
      3183593.38     13806244.01     3184284.956     13800307.97
     3184419.797    13799150.582     3184628.482    13798161.474
     3184630.541    13798111.569     3184667.007     13796779.62
#Sta/Elev= 30
 2494.06   34.92 4707.37   35.67 5085.03    32.8 5116.03   25.51 5124.74   25.82
    5135    32.2 5247.56   35.15 6271.92   31.41 8032.49   34.77 8569.42    31.1
 8839.36    33.1  9729.7   30.55 9869.11   28.94 9883.09   26.23 10060.3   30.93
10315.51   28.4410332.93   31.2210374.28   29.0910631.08   33.6210675.34   25.84
10711.52   31.8710798.52   29.8910890.01   34.0211432.45   33.6511541.86    30.9
11717.75   33.7511770.77    30.511800.78   33.3411845.79   30.6612028.74   33.75
#Mann= 4 ,-1 , 0
 2494.06     .15       0 8032.49     .12       010631.08    .032       0
10890.01     .12       0
#Block Obstruct= 3 ,-1
 2109.52 8258.15   35.21 4793.56 5225.49   34.93 8838.1410625.29   33.06
Bank Sta=10631.08,10890.01
XS Rating Curve= 0 ,0
Exp/Cntr=0.3,0.1

Type RM Length L Ch R = 1 ,17690.78,37.75,39.73,42.28
XS GIS Cut Line= 6
     3183718.929    13806248.848     3184430.473    13799232.279
      3184652.29    13798721.135     3185083.131    13798170.616
     3185085.928    13798127.025     3185565.949    13797745.983
#Sta/Elev= 30
       0   35.29 483.105   35.85 775.351   32.81 964.036    35.31027.462   32.94
1120.638   35.85 1287.55   33.781372.794   36.281411.911   33.351593.169   35.83
1932.917   33.032287.887   35.96 2834.32   31.434125.583   34.374380.614   34.79
4446.236    32.14556.959   33.474575.261   31.185474.648   32.155525.539   27.97
5589.719   31.61 6021.73   30.746249.773   33.236284.973   23.536301.357    30.6
6333.485   32.536353.409    37.66376.821   32.396418.979   31.026766.258   31.75
#Mann= 4 ,-1 , 0
       0     .15       04125.583     .12       06249.773    .032       0
6333.485     .12       0
#Block Obstruct= 3 ,-1
 -88.5584270.457   35.01  50.9284532.333   30.395478.9355593.236    31.6
Bank Sta=6249.773,6333.485
XS Rating Curve= 0 ,0
Skew Angle= 41
Exp/Cntr=0.5,0.3

Type RM Length L Ch R = 1 ,17651.05,72.46,112.44,136.64
XS GIS Cut Line= 6
     3183807.125    13806252.246     3184469.558    13799242.692
     3184687.062    13798741.488      3185122.99    13798167.637
     3185125.893    13798128.985     3185565.949     13797790.93
#Sta/Elev= 30
       0   35.55 498.357   35.49  768.43   32.43 958.459   35.631049.688   32.83
1230.161   36.051288.531    33.4 1311.27   36.33 1368.13   36.411405.503   33.09
1580.392   35.742141.692   32.472289.185   35.83 2493.81   32.282587.009   34.12
2834.999   31.663448.955   32.153524.433   34.58 4097.19   32.254218.117   34.36
5424.974   29.245499.018   31.646246.415   32.61 6262.62   27.57 6262.62   21.89
6274.807   21.79 6296.31   21.826297.583    30.56335.878   32.446718.025   31.48
#Mann= 4 ,-1 , 0
       0     .15       04218.117     .12       06246.415    .032       0
6335.878     .12       0
#XS Ineff= 2 ,-1
 5269.796263.886   31.026294.2786718.025      31
Permanent Ineff=
       F       F
#Block Obstruct= 1 ,-1
 -29.5174329.498   34.75
Bank Sta=6246.415,6335.878
XS Rating Curve= 0 ,0
Skew Angle= 41
Exp/Cntr=0.5,0.3

Type RM Length L Ch R = 2 ,17594.83,,,
BEGIN DESCRIPTION:
Preston West
END DESCRIPTION:
Bridge Culvert--1,0,-1,-1, 0
Deck Dist Width WeirC Skew NumUp NumDn MinLoCord MaxHiCord MaxSubmerge Is_Ogee
61,47,2.6,41, 8, 8, , , 0.95, 0, 0,0,,
4396.1845905.6036228.6186260.7086299.3126341.8256641.4446660.312
    32.8      31      32   34.27   34.27    32.6    31.2    31.4
                                                                
4427.881  5937.36260.3166292.406 6331.016373.5226673.142 6692.01
    32.8      31      32   34.27   34.27    32.6    31.2    31.4
                                                                
Culvert=2,8,12.5,47,0.012,0.7,1,58,1,21.86,6273,21.86,6301,Culvert #1  , 0 ,61
Culvert Bottom n=0.012
Culvert=2,8,13.5,47,0.012,0.7,1,58,1,21.86,6287,21.86,6315,Culvert #2  , 0 ,61
Culvert Bottom n=0.012
BC Design=,, 0 ,, 0 ,,,,,,
BC HTab HWMax=36.41
BC Use User HTab Curves=0
BC User HTab FreeFlow(D)= 0

Type RM Length L Ch R = 1 ,17538.61,83.07,62.49,51.68
XS GIS Cut Line= 6
     3183973.965    13806280.396     3184484.082    13799525.991
     3184757.886    13798773.368     3184956.217    13798456.108
       3185153.3    13798230.869     3185608.061     13797863.85
#Sta/Elev= 30
       0   34.86 495.444   35.61   568.5   33.26 637.903   35.53 785.622   32.51
 967.938   35.491065.642   32.251105.982   35.311236.652   35.961303.142   33.13
1330.621   36.11 1421.45   32.441647.924   35.252115.285   32.472306.634   35.47
2503.032   31.983654.123   33.884203.204   31.425365.933   31.645498.965   27.95
5718.186    30.86144.574   29.176208.325   32.056260.044   25.756283.938    26.6
6293.297   21.816328.074   21.816335.523    26.76387.704   33.21 6667.52   32.01
#Mann= 4 ,-1 , 0
       0     .15       04203.204     .12       06208.325    .032       0
6387.704     .12       0
#XS Ineff= 5 ,-1
       01343.308   36.091364.6962311.079   35.612450.0973653.119   33.88
 6328.24 6667.52      314566.8386293.456   30.96
Permanent Ineff=
       F       F       F       F       F
Bank Sta=6208.325,6387.704
XS Rating Curve= 0 ,0
Skew Angle= 41
Exp/Cntr=0.5,0.3

Type RM Length L Ch R = 1 ,17476.12,95.06,103.62,96.5
XS GIS Cut Line= 6
     3184002.705    13806259.782     3184577.209    13799532.489
     3184655.176     13799205.46     3184834.934    13798798.297
     3185268.676    13798191.143     3185621.937    13797871.418
#Sta/Elev= 30
       0   34.72 475.324   35.64 553.519   33.21 617.118   35.56 770.543   32.71
 943.108   35.071047.658   32.03 1234.69   35.641281.829   32.691331.293   35.95
1402.764   32.261563.947   34.772762.698   32.183395.137   26.753417.861   27.51
3439.453   32.683477.589    27.33546.033   25.574192.102   28.984490.311   33.11
6161.525   30.936161.729   30.93 6242.18   26.916258.264   25.21 6260.82   20.94
6275.674    20.7 6323.58   20.88 6323.58   30.966332.587    33.16608.509   32.24
#Mann= 4 ,-1 , 0
       0     .15       04192.102     .12       06161.525    .032       0
6332.587     .12       0
#XS Ineff= 4 ,-1
       01332.998   35.921369.4731564.438   34.775381.713 6261.91    30.5
 6323.216608.509    30.5
Permanent Ineff=
       F       F       F       F
#Block Obstruct= 3 ,-1
 -40.7396161.932   30.83  656.43 1539.25   32.76 1692.98 4483.66   32.79
Bank Sta=6161.729,6332.587
XS Rating Curve= 0 ,0
Skew Angle= 41
Exp/Cntr=0.5,0.3

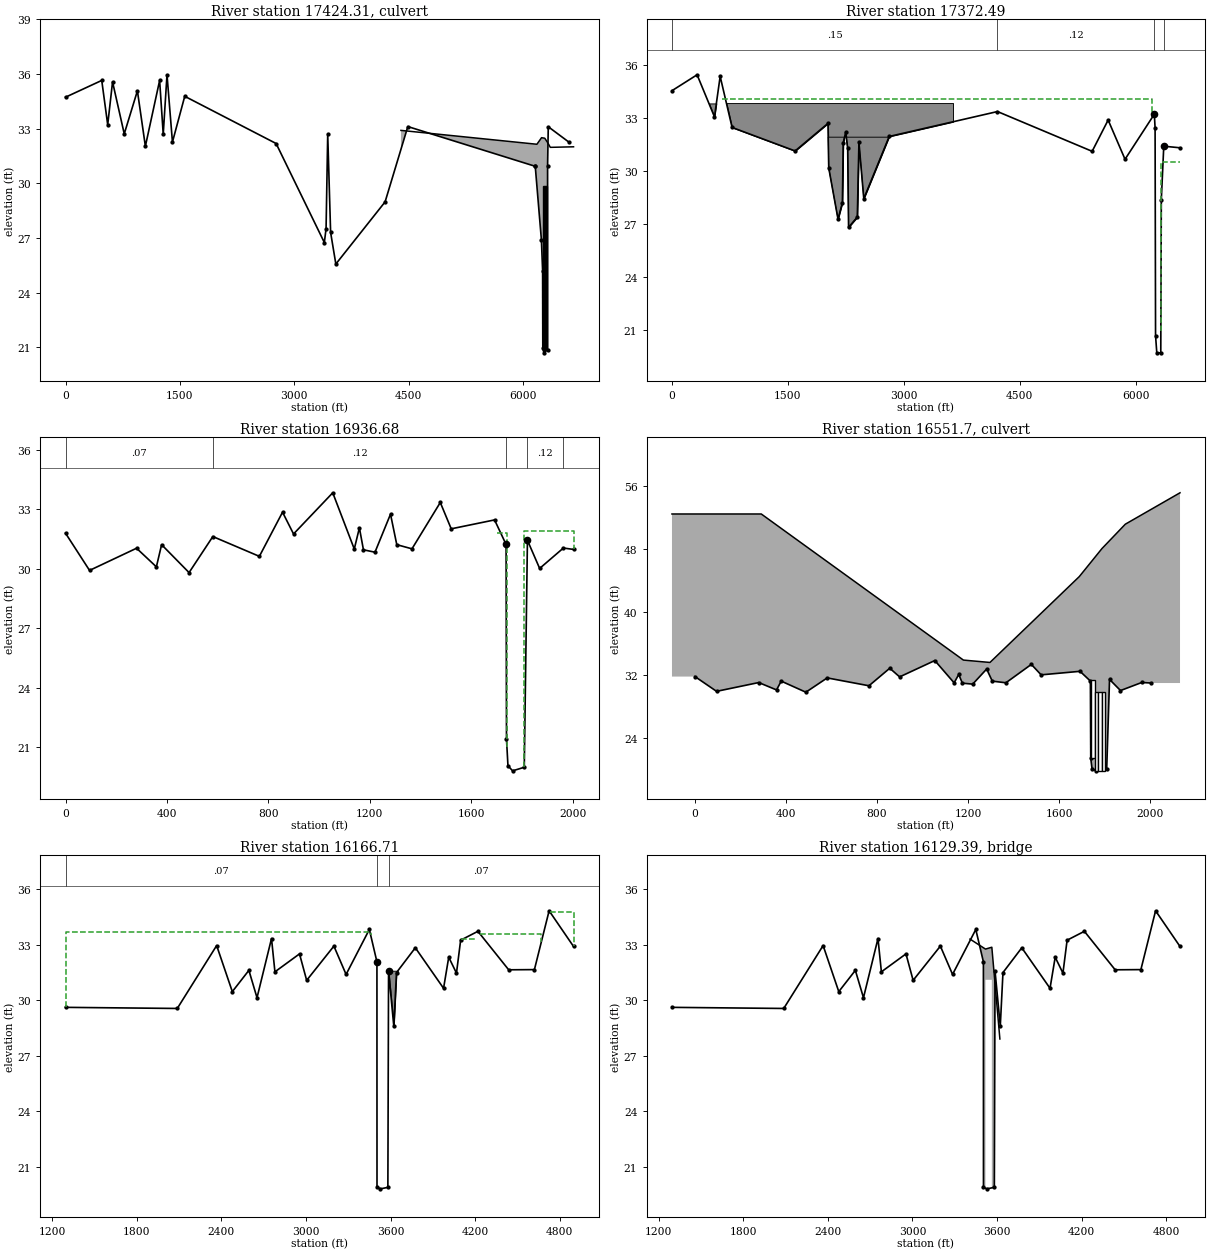
Type RM Length L Ch R = 2 ,17424.31,,,
BEGIN DESCRIPTION:
Preston East
END DESCRIPTION:
Bridge Culvert--1,0,-1,-1, 0
Deck Dist Width WeirC Skew NumUp NumDn MinLoCord MaxHiCord MaxSubmerge Is_Ogee
16,47,2.6,41, 7, 7, , , 0.95, 0, 0,0,,
 4399.96 6183.34 6244.47 6286.73    6329 6359.18 6664.09
    32.9   32.14    32.5   32.47    32.2   31.97      32
                                                        
 4399.96 6183.34 6244.47 6286.73    6329 6359.18 6664.09
    32.9   32.14    32.5   32.47    32.2   31.97      32
                                                        
Multiple Barrel Culv=2,9,10,47,0.012,0.5,1,8,1,20.83,20.83, 4,Culvert #1  , 0 ,16
    6270    6275    6285    6290    6300    6305    6313    6318
Culvert Bottom n=0.012
BC Design=,, 0 ,, 0 ,,,,,,
BC HTab HWMax=35.95
BC Use User HTab Curves=0
BC User HTab FreeFlow(D)= 0

Type RM Length L Ch R = 1 ,17372.49,587.71,435.81,262.88
XS GIS Cut Line= 6
     3184028.582    13806260.779     3184588.571    13800335.278
     3184689.906    13799263.006     3184874.016    13798838.752
     3185330.196    13798238.242     3185661.958    13797915.366
#Sta/Elev= 30
       0   34.56  324.94   35.46 549.866   33.08 623.383   35.37 777.751   32.48
1593.011   31.15 2017.95   32.712028.018   30.192148.251   27.292204.688   28.22
2216.054   31.622247.329   32.212273.117    31.32284.619   26.832397.773   27.41
2418.754   31.632481.553   28.452810.523   31.974211.023   33.385435.683   31.13
5642.549    32.95861.082   30.686240.037   33.236249.969   32.466255.969    20.7
 6272.12   19.736323.448   19.736330.504    28.46362.307   31.426572.389   31.33
#Mann= 4 ,-1 , 0
       0     .15       04211.023     .12       06240.037    .032       0
6362.307     .12       0
#XS Ineff= 2 ,-1
 641.654 6212.86    34.16324.4666572.389    30.5
Permanent Ineff=
       F       F
#Block Obstruct= 3 ,-1
  445.96  660.98   33.84 662.0243636.048   33.86 1996.262821.248   31.93
Bank Sta=6240.037,6362.307
XS Rating Curve= 0 ,0
Skew Angle= 41
Exp/Cntr=0.5,0.3

Type RM Length L Ch R = 1 ,16936.68,757.96,769.97,772.46
XS GIS Cut Line= 4
     3187468.335    13800096.877     3185835.388    13798229.409
     3185837.907     13798180.18     3185644.569    13797946.666
#Sta/Elev= 30
       0    31.8  94.802   29.92 280.191   31.04 358.348    30.1 378.931   31.22
 487.225   29.81 580.973   31.63 764.453   30.63 855.847   32.86 899.199   31.76
1053.815   33.841138.703      31 1158.87   32.071174.865   30.961220.339   30.84
1281.574   32.761306.323   31.221366.201   31.011477.896   33.351520.973   32.02
1691.894   32.471737.368   31.231738.945    21.4  1744.7   20.061763.022    19.8
 1809.05   19.981821.528   31.441869.696   30.021963.289   31.052003.354   30.98
#Mann= 5 ,-1 , 0
       0     .07       0 580.973     .12       01737.368    .032       0
1821.528     .12       01963.289     .07       0
#XS Ineff= 2 ,-1
1700.493  1740.6   31.79 1807.012003.354   31.92
Permanent Ineff=
       F       F
Bank Sta=1737.368,1821.528
XS Rating Curve= 0 ,0
Skew Angle= 45
Exp/Cntr=0.5,0.3

Type RM Length L Ch R = 2 ,16551.7 ,,,
BEGIN DESCRIPTION:
Sam Houston Toll Road
END DESCRIPTION:
Bridge Culvert--1,0,-1,-1, 0
Deck Dist Width WeirC Skew NumUp NumDn MinLoCord MaxHiCord MaxSubmerge Is_Ogee
70,564,2.6,45, 8, 10, , , 0.95, 0, 0,0,,
-101.116 291.3281179.4541296.1271688.5711788.2731890.803 2131.22
    52.5    52.5    33.9    33.6   44.53    48.1    51.2    55.2
                                                                
 1060.661646.1452038.5893043.3873435.8323535.5343638.0643878.481 4135.165945.354
      38    52.5    52.5    33.6   44.53    48.1    51.2    55.2    54.8    38.3
                                                                                
Culvert=2,10,14,564,0.012,0.5,1,58,1,21.42,1749,21.42,3520,Culvert #1  , 0 ,70
Culvert Bottom n=0.012
Multiple Barrel Culv=2,10,15,564,0.012,0.5,1,58,1,19.8,19.8, 3,Culvert #2  , 0 ,70
 1764.24 3535.24 1780.24 3551.24 1796.24 3567.24
Culvert Bottom n=0.012
BC Design=,, 0 ,, 0 ,,,,,,
BC HTab HWMax=33.84
BC Use User HTab Curves=0
BC User HTab FreeFlow(D)= 0

Type RM Length L Ch R = 1 ,16166.71,61.78,74.65,81.03
XS GIS Cut Line= 5
      3188606.08     13800704.83     3187837.049    13799679.455
     3186610.901    13798304.983     3186599.064    13798214.913
     3185336.812    13796820.099
#Sta/Elev= 30
1294.373   29.612087.026   29.552366.319   32.952477.419   30.462594.969   31.61
2652.555   30.132755.397   33.332779.623   31.532953.981    32.53004.716   31.07
 3197.89   32.923284.363   31.39 3449.21   33.823503.106   32.07 3503.59   19.88
 3528.18    19.8 3580.69   19.883585.569   31.583622.777   28.59 3641.89   31.49
3775.377   32.833975.623   30.644012.265   32.324067.215   31.464096.765   33.24
4219.278   33.724437.484   31.644620.017   31.654724.258   34.834897.527    32.9
#Mann= 3 , 0 , 0
1294.373     .07       03503.106    .032       03585.569     .07       0
#XS Ineff= 5 ,-1
1294.3733458.311   33.683776.8694095.428   32.74 4105.084211.266   33.28
  4235.44669.804   33.584727.7234897.527   34.79
Permanent Ineff=
       F       F       F       F       F
#Block Obstruct= 1 ,-1
3585.6043656.081   31.59
Bank Sta=3503.106,3585.569
XS Rating Curve= 0 ,0
Skew Angle= 45
Exp/Cntr=0.5,0.3

Type RM Length L Ch R = 3 ,16129.39,,,
BEGIN DESCRIPTION:
Wood Brige DS of Sam Houston Toll Road
END DESCRIPTION:
Bridge Culvert--1,0,-1,-1, 0
Deck Dist Width WeirC Skew NumUp NumDn MinLoCord MaxHiCord MaxSubmerge Is_Ogee
35,11,2.6,0, 4, 4, , , 0.95, 0, 0,0,,
    3408 3517.85 3562.91    3620
    33.3   32.76   32.86    27.9
            31.1    31.1
    4950 4999.85 5044.91    5102
    33.3   32.76   32.86    27.9
            31.1    31.1
Pier Skew, UpSta & Num, DnSta & Num=  ,3526, 2 ,5015.009, 2 , 0 , 0 , 0 ,,
       1       1
       0
       1       1
       0
Pier Skew, UpSta & Num, DnSta & Num=  ,3540, 2 ,5029.432, 2 , 0 , 0 , 0 ,,
       1       1
       0
       1       1
       0
BR Coef=-1 , 1 , 0 ,, 0 ,,,0.8,0,1.2,0,
WSPro=,,,, 1 ,,,, 0 ,,,, 0 ,,,,-1 ,-1 ,-1 , 0 , 0 , 0 , 0 , 0
BC Design=,, 0 ,, 0 ,,,,,,
BC HTab HWMax=34.83
BC Use User HTab Curves=0
BC User HTab FreeFlow(D)= 0

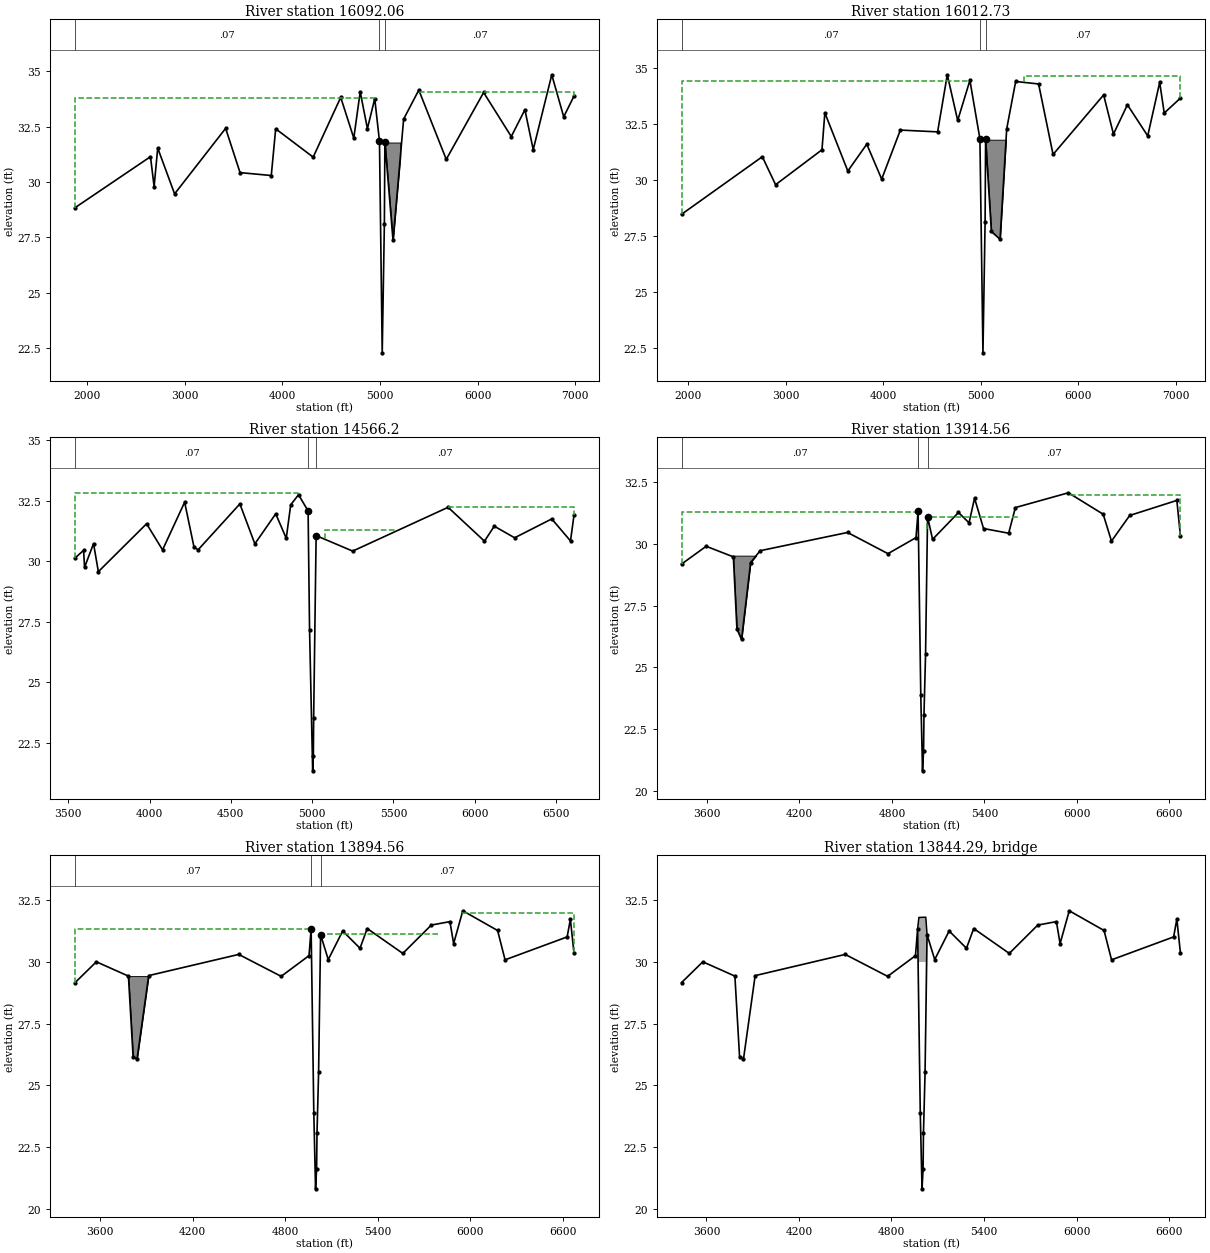
Type RM Length L Ch R = 1 ,16092.06,76.8,79.32,80.24
XS GIS Cut Line= 5
      3188662.08     13800662.83     3187891.264    13799635.076
     3186683.958     13798320.19     3186674.797    13798217.011
     3185388.714    13796773.129
#Sta/Elev= 30
 1879.65   28.85 2650.61   31.15 2687.85    29.8  2724.7   31.54 2897.58   29.47
 3419.96   32.43 3567.68   30.43 3887.26    30.3 3932.51   32.41 4316.25   31.13
  4598.2   33.83 4732.06   31.99 4797.71   34.08 4871.52   32.42 4946.61   33.77
    4995   31.85 5023.18   22.29 5045.21   28.12 5050.42   31.82 5133.66   27.37
 5242.53   32.85 5397.76   34.16 5678.69   31.03 6061.28   34.05 6344.32   32.06
 6483.79   33.27 6569.11   31.47 6758.96   34.85 6881.27   32.95 6986.61   33.89
#Mann= 3 , 0 , 0
 1879.65     .07       0    4995    .032       0 5050.42     .07       0
#XS Ineff= 2 ,-1
 1879.65 4945.39   33.78 5409.56 6986.61   34.09
Permanent Ineff=
       F       F
#Block Obstruct= 1 ,-1
 5051.86 5207.91   31.79
Bank Sta=4995,5050.42
XS Rating Curve= 0 ,0
Exp/Cntr=0.5,0.3

Type RM Length L Ch R = 1 ,16012.73,1413.43,1446.53,1525.45
XS GIS Cut Line= 5
      3188726.08     13800614.83      3187952.88    13799583.897
     3186762.548    13798332.726     3186754.833    13798222.315
     3185448.453    13796719.919
#Sta/Elev= 30
 1932.23   28.48 2759.74   31.05  2896.1    29.8  3371.8   31.36 3401.39   33.01
 3636.98   30.41 3831.47   31.61 3984.36   30.05 4175.96   32.24 4558.02   32.16
 4657.46   34.71    4764   32.67 4889.47   34.46    4992   31.85 5023.18   22.29
 5045.21   28.12 5050.42   31.82 5109.67   27.71 5198.81   27.36 5266.71   32.29
 5358.83   34.41 5594.04    34.3 5742.41   31.15 6261.34   33.81 6361.86   32.06
 6505.15   33.37 6713.53   31.98 6836.29   34.37 6882.84      33 7049.45   33.67
#Mann= 3 ,-1 , 0
 1932.23     .07       0    4992    .032       0 5050.42     .07       0
#XS Ineff= 2 ,-1
 5443.69 7049.45   34.64 1932.23 4886.23   34.43
Permanent Ineff=
       F       F
#Block Obstruct= 1 ,-1
 5050.98 5264.46   31.81
Bank Sta=4992,5050.42
XS Rating Curve= 0 ,0
Exp/Cntr=0.3,0.1

Type RM Length L Ch R = 1 ,14566.2 ,636.15,651.64,647.86
XS GIS Cut Line= 4
     3188285.972    13799999.378     3188168.302    13798570.965
     3188178.054    13798522.524     3188392.641    13796950.416
#Sta/Elev= 30
 3542.06   30.13 3593.81   30.44 3599.85   29.74 3655.08   30.72 3684.73   29.56
 3981.47   31.54 4079.74   30.46 4215.64   32.43 4272.84   30.59 4298.01   30.46
 4555.43   32.36 4647.66   30.71 4776.04   31.95 4840.85   30.94 4868.21   32.32
 4916.28   32.74 4975.29   32.07 4984.19   27.17  5003.4   21.33 5007.62   21.96
 5009.48   23.53 5024.71   31.05 5249.76   30.41 5836.55   32.22 6060.49   30.82
 6120.75   31.44 6246.06   30.96 6474.53   31.74 6589.84   30.83 6611.41    31.9
#Mann= 3 ,-1 , 0
 3542.06     .07       0 4975.29    .032       0 5024.71     .07       0
#XS Ineff= 3 ,-1
 3542.06 4913.54   32.82 5837.31 6611.41   32.22 5076.79 5510.81   31.28
Permanent Ineff=
       F       F       F
Bank Sta=4975.29,5024.71
XS Rating Curve= 0 ,0
Exp/Cntr=0.3,0.1

Type RM Length L Ch R = 1 ,13914.56,20.55,20,20.34
XS GIS Cut Line= 4
     3188614.094    13800226.965     3188804.631    13798707.341
     3188818.815    13798644.707     3188927.593    13797008.337
#Sta/Elev= 30
 3435.53   29.19 3594.69   29.91 3770.99   29.48 3794.18   26.55 3824.12   26.13
 3882.92   29.25 3944.95   29.73 4511.81   30.47 4773.93   29.61 4955.71   30.26
  4969.3   31.34 4986.75   23.87 4998.01    20.8 5004.77   21.59 5007.45   23.07
 5017.74   25.52  5030.7   31.11 5063.15   30.19 5231.35   31.28  5299.8   30.86
 5335.52   31.86 5393.78   30.63 5556.75   30.44 5600.43   31.48 5944.39   32.08
 6169.87   31.21 6223.79   30.12 6341.99   31.16 6647.75   31.77 6671.25   30.31
#Mann= 3 , 0 , 0
 3435.53     .07       0  4969.3    .032       0  5030.7     .07       0
#XS Ineff= 3 ,-1
 3435.53 4967.97    31.3 5029.58 5616.61    31.1 5953.36 6671.25   32.01
Permanent Ineff=
       F       F       F
#Block Obstruct= 1 ,-1
 3764.51 3955.63   29.53
Bank Sta=4969.3,5030.7
XS Rating Curve= 0 ,0
Exp/Cntr=0.5,0.3

Type RM Length L Ch R = 1 ,13894.56,104.84,100.55,101.91
XS GIS Cut Line= 4
     3188638.742    13800226.965     3188825.036    13798707.787
     3188838.598    13798647.902     3188951.871    13797008.337
#Sta/Elev= 30
 3438.91   29.17 3576.29   30.01 3784.31   29.43 3814.72   26.15 3840.03   26.06
 3915.74   29.45 4499.81   30.31 4774.96   29.42 4955.71   30.26  4969.3   31.34
 4986.75   23.87 4998.01    20.8 5004.77   21.59 5007.45   23.07 5017.74   25.52
  5030.7   31.11 5080.36    30.1 5173.99   31.26 5286.29   30.56 5333.26   31.36
 5563.99   30.35 5748.69    31.5 5869.47   31.64 5893.57   30.75 5953.06   32.08
 6178.73   31.28 6227.22   30.09 6629.92   31.02 6650.84   31.74 6674.34   30.35
#Mann= 3 ,-1 , 0
 3438.91     .07       0  4969.3    .032       0  5030.7     .07       0
#XS Ineff= 3 ,-1
 5948.81 6674.34   32.01 3438.91 4968.07   31.33 5034.13 5794.08   31.13
Permanent Ineff=
       F       F       F
#Block Obstruct= 1 ,-1
  3755.4 3919.23   29.43
Bank Sta=4969.3,5030.7
XS Rating Curve= 0 ,0
Exp/Cntr=0.5,0.3

Type RM Length L Ch R = 3 ,13844.29,,,
BEGIN DESCRIPTION:
Wooden Vehicular Bridge
END DESCRIPTION:
Bridge Culvert--1,0,-1,-1, 0
Deck Dist Width WeirC Skew NumUp NumDn MinLoCord MaxHiCord MaxSubmerge Is_Ogee
42,11,2.6,0, 4, 4, , , 0.95, 0, 0,0,,
  4969.3 4977.62 5022.44  5030.7
   31.34   31.81   31.82   31.11
              30      30
  4969.3 4977.62 5022.44  5030.7
   31.34   31.81   31.82   31.11
              30      30
Pier Skew, UpSta & Num, DnSta & Num=  ,4992.225, 2 ,4992.225, 2 , 0 , 0 , 0 ,,
       1       1
       0
       1       1
       0
Pier Skew, UpSta & Num, DnSta & Num=  ,5006.777, 2 ,5006.777, 2 , 0 , 0 , 0 ,,
       1       1
       0
       1       1
       0
BR Coef=-1 , 1 , 0 ,, 0 ,,,0.8,0,1.2,0,
WSPro=,,,, 1 ,,,, 0 ,,,, 0 ,,,,-1 ,-1 ,-1 , 0 , 0 , 0 , 0 , 0
BC Design=,, 0 ,, 0 ,,,,,,
BC HTab HWMax=32.08
BC Use User HTab Curves=0
BC User HTab FreeFlow(D)= 0

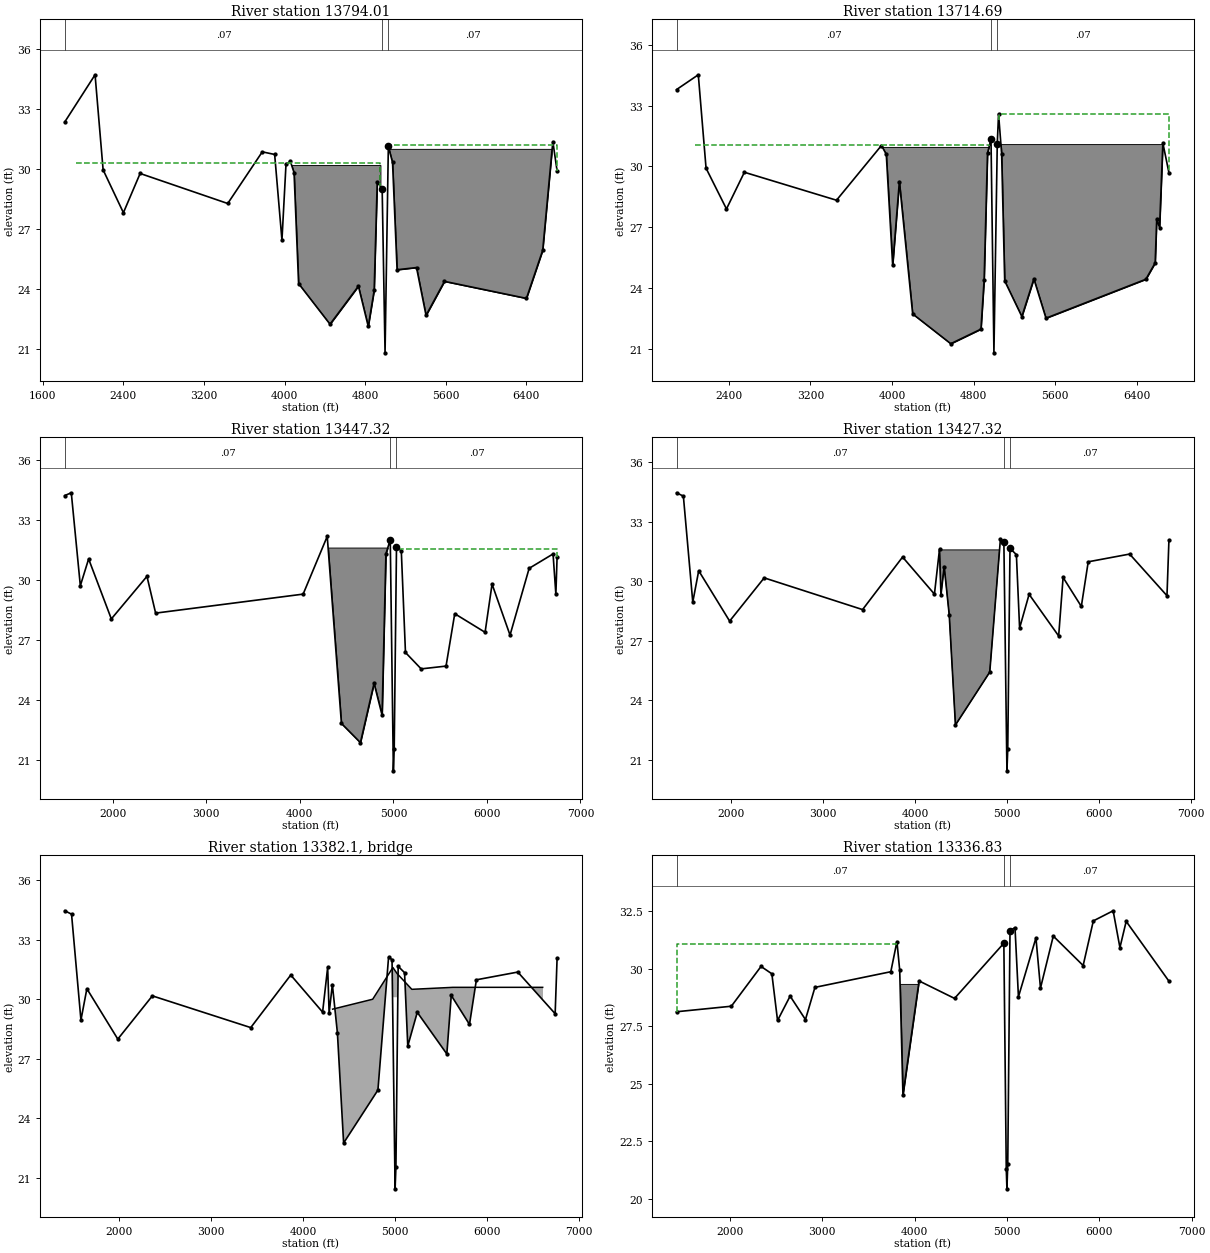
Type RM Length L Ch R = 1 ,13794.01,75.7,79.32,80.26
XS GIS Cut Line= 5
     3188728.657    13801873.087     3188866.734    13800066.754
     3188921.898    13798738.472     3188937.512    13798663.881
     3189081.354    13797000.244
#Sta/Elev= 30
 1818.51   32.33 2119.69   34.69  2199.6   29.94 2400.99    27.8 2566.92   29.76
 3436.39   28.26 3779.35   30.84 3902.28   30.71 3974.66   26.43  4014.9   30.23
 4058.71   30.36 4094.77    29.8 4139.81   24.26 4451.73   22.23 4733.69   24.13
 4831.32   22.12 4890.07   23.92 4920.48   29.32  4969.3      29 4998.01    20.8
  5030.7   31.11 5072.26   30.31 5117.43   24.95 5310.37   25.06 5404.88   22.67
 5587.89   24.37 6401.23   23.52  6562.8   25.92  6663.4   31.35 6705.59   29.89
#Mann= 3 , 0 , 0
 1818.51     .07       0  4969.3    .032       0  5030.7     .07       0
#XS Ineff= 2 ,-1
 1928.33 4952.22    30.3 5034.13 6705.59   31.19
Permanent Ineff=
       F       F
#Block Obstruct= 2 ,-1
 4044.37 4952.22   30.18 5034.13 6651.88   30.99
Bank Sta=4969.3,5030.7
XS Rating Curve= 0 ,0
Exp/Cntr=0.5,0.3

Type RM Length L Ch R = 1 ,13714.69,268.69,267.37,263.65
XS GIS Cut Line= 5
     3188746.523    13801816.118     3188891.381     13800054.43
     3188998.053    13798757.138     3189016.643    13798676.664
     3189154.188    13797008.337
#Sta/Elev= 30
  1887.3   33.79 2100.41   34.52 2176.45   29.91 2376.58    27.9 2552.03   29.71
 3455.06   28.33 3895.51   31.03 3942.83    30.6 4005.67   25.12 4071.26   29.25
 4201.53   22.72 4574.96   21.25 4871.04   21.97 4902.04   24.39 4935.22   30.66
  4969.3   31.34 4998.01    20.8  5030.7   31.11 5043.38   32.59 5073.48   30.63
 5103.58   24.35 5271.77   22.59 5389.55   24.45 5508.16   22.51 6487.15   24.43
 6578.57   25.24 6593.62   27.39 6621.63   26.98 6653.82   31.15 6713.19   29.69
#Mann= 3 , 0 , 0
  1887.3     .07       0  4969.3    .032       0  5030.7     .07       0
#XS Ineff= 2 ,-1
 2071.54 4952.03   31.06 5047.78 6713.19   32.57
Permanent Ineff=
       F       F
#Block Obstruct= 2 ,-1
  3894.2 4959.04   30.96 5047.78 6651.88    31.1
Bank Sta=4969.3,5030.7
XS Rating Curve= 0 ,0
Exp/Cntr=0.3,0.1

Type RM Length L Ch R = 1 ,13447.32,20.52,20,19.9
XS GIS Cut Line= 5
     3188898.088    13802264.076     3189100.887    13800344.042
      3189263.39    13798805.518     3189275.421    13798737.651
     3189396.969    13797024.522
#Sta/Elev= 30
 1486.18   34.21 1556.32   34.35 1653.08    29.7 1741.74   31.04 1984.53   28.04
 2365.44   30.17 2458.13   28.33 4035.19   29.28 4292.88   32.17 4444.64   22.81
 4647.59   21.85 4793.57   24.82 4879.51   23.22 4920.44    31.3 4966.61      32
 4999.95   20.44 5008.89   21.52 5033.39   31.66 5084.77   31.44 5129.24   26.36
 5297.04   25.54 5563.02   25.68  5656.1    28.3 5980.47   27.37 6055.09   29.78
 6247.23   27.23 6451.61   30.57 6707.25   31.29 6737.33   29.27 6750.34   31.14
#Mann= 3 , 0 , 0
 1486.18     .07       0 4966.61    .032       0 5033.39     .07       0
#XS Ineff= 2 ,-1
 1486.18 4952.24    30.9 5054.61 6750.34   31.55
Permanent Ineff=
       F       F
#Block Obstruct= 1 ,-1
 4296.93 4945.39   31.61
Bank Sta=4966.61,5033.39
XS Rating Curve= 0 ,0
Exp/Cntr=0.5,0.3

Type RM Length L Ch R = 1 ,13427.32,91.63,90.49,91.88
XS GIS Cut Line= 5
     3188927.714    13802351.637     3189131.697    13800319.394
     3189283.582    13798806.193      3189295.24    13798740.432
     3189413.154     13797016.43
#Sta/Elev= 30
 1404.73   34.46 1478.98   34.29 1581.23   28.95 1645.78   30.53 1982.36   27.99
 2358.45   30.17 3428.99   28.57 3864.43   31.22 4211.07   29.35 4266.19   31.61
 4281.97    29.3 4317.33   30.74 4372.13    28.3 4439.78   22.75  4813.1   25.42
 4928.79   32.11 4966.61      32 4999.95   20.44 5008.89   21.52 5033.39   31.66
 5102.87   31.34  5137.9   27.64 5241.24   29.34 5562.99   27.24 5611.12   30.19
 5809.51   28.73 5884.69   30.98 6335.25   31.37 6741.69   29.27 6762.81   32.06
#Mann= 3 , 0 , 0
 1404.73     .07       0 4966.61    .032       0 5033.39     .07       0
#XS Ineff= 2 ,-1
 1484.64 4938.57      31 5068.26 6762.81      31
Permanent Ineff=
       F       F
#Block Obstruct= 1 ,-1
  4262.8 4945.39   31.58
Bank Sta=4966.61,5033.39
XS Rating Curve= 0 ,0
Exp/Cntr=0.5,0.3

Type RM Length L Ch R = 3 ,13382.1 ,,,
BEGIN DESCRIPTION:
Wooden Vehicular Bridge
END DESCRIPTION:
Bridge Culvert--1,0,-1,-1, 0
Deck Dist Width WeirC Skew NumUp NumDn MinLoCord MaxHiCord MaxSubmerge Is_Ogee
52,10,2.6,0, 7, 7, , , 0.95, 0, 0,0,,
    4320    4756 4975.78 5022.45    5182    5629    6606
    29.5      30    31.6   31.29    30.5    30.6    30.6
                    30.1    30.1
    4320    4756 4975.78 5022.45    5182    5629    6606
    29.5      30    31.6   31.29    30.5    30.6    30.6
                    30.1    30.1
Pier Skew, UpSta & Num, DnSta & Num=  ,4991.192, 2 ,4991.192, 2 , 0 , 0 , 0 ,,
       1       1
       0
       1       1
       0
Pier Skew, UpSta & Num, DnSta & Num=  ,5006.15, 2 ,5006.15, 2 , 0 , 0 , 0 ,,
       1       1
       0
       1       1
       0
BR Coef=-1 , 1 , 0 ,, 0 ,,,0.8,-1,2,0,
WSPro=,,,, 1 ,,,, 0 ,,,, 0 ,,,,-1 ,-1 ,-1 , 0 , 0 , 0 , 0 , 0
BC Design=,, 0 ,, 0 ,,,,,,
BC HTab HWMax=34.62
BC Use User HTab Curves=0
BC User HTab FreeFlow(D)= 0

Type RM Length L Ch R = 1 ,13336.83,82.06,87.53,92.74
XS GIS Cut Line= 5
     3189097.368     13802356.14     3189254.936    13800331.718
     3189369.724    13798856.927     3189388.632    13798715.661
     3189494.081    13797040.708
#Sta/Elev= 30
 1423.18   28.14 2016.37   28.38 2337.77   30.11 2454.93   29.79 2516.55   27.76
 2652.64   28.82 2818.66    27.8 2921.34    29.2 3742.87   29.88 3809.01   31.19
 3839.11   29.95 3874.19   24.52 4048.76   29.48 4432.85   28.72 4966.61   31.12
 4992.83    21.3 4999.95   20.44 5008.89   21.52 5033.39   31.66 5087.31    31.8
 5124.55   28.79 5314.14   31.35 5363.27   29.17 5501.77   31.43 5825.14   30.15
 5935.31   32.09 6149.88   32.53 6223.29   30.93 6291.07   32.07 6753.77   29.47
#Mann= 3 , 0 , 0
 1423.18     .07       0 4966.61    .032       0 5033.39     .07       0
#XS Ineff= 2 ,-1
 1423.18 3808.32    31.1 3818.18 4846.15   30.47
Permanent Ineff=
       F       F
#Block Obstruct= 1 ,-1
 3798.63 4064.85   29.35
Bank Sta=4966.61,5033.39
XS Rating Curve= 0 ,0
Exp/Cntr=0.5,0.3