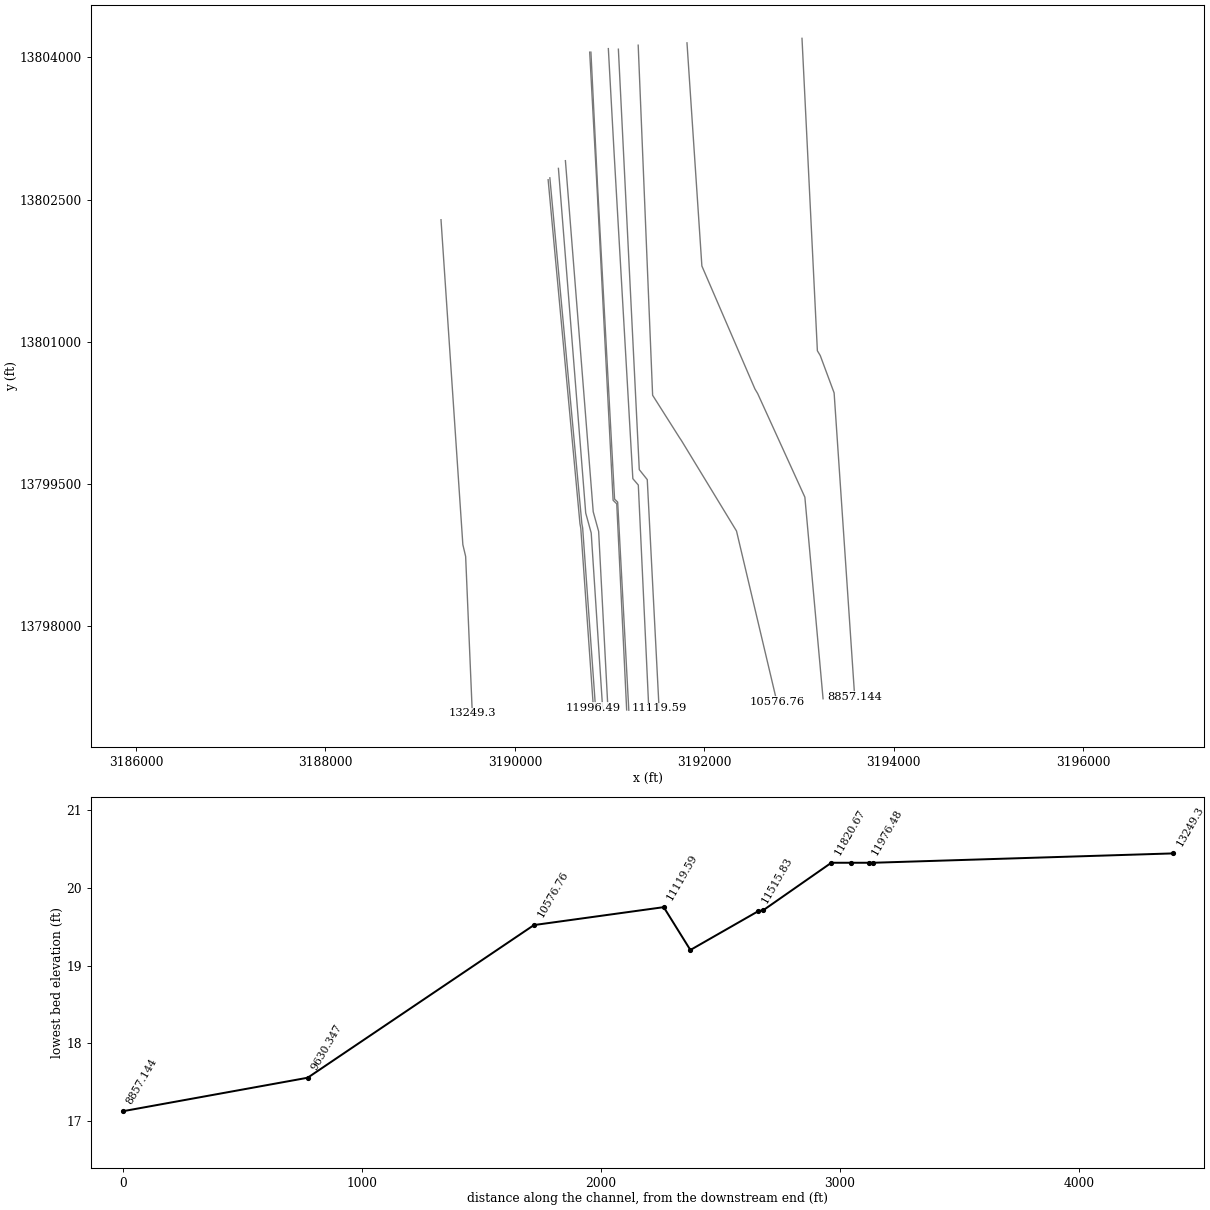
HEC-RAS study B113-00-00.prj: B113-00-00

--- B113-00-00.g01 (geometry) --- (continued)

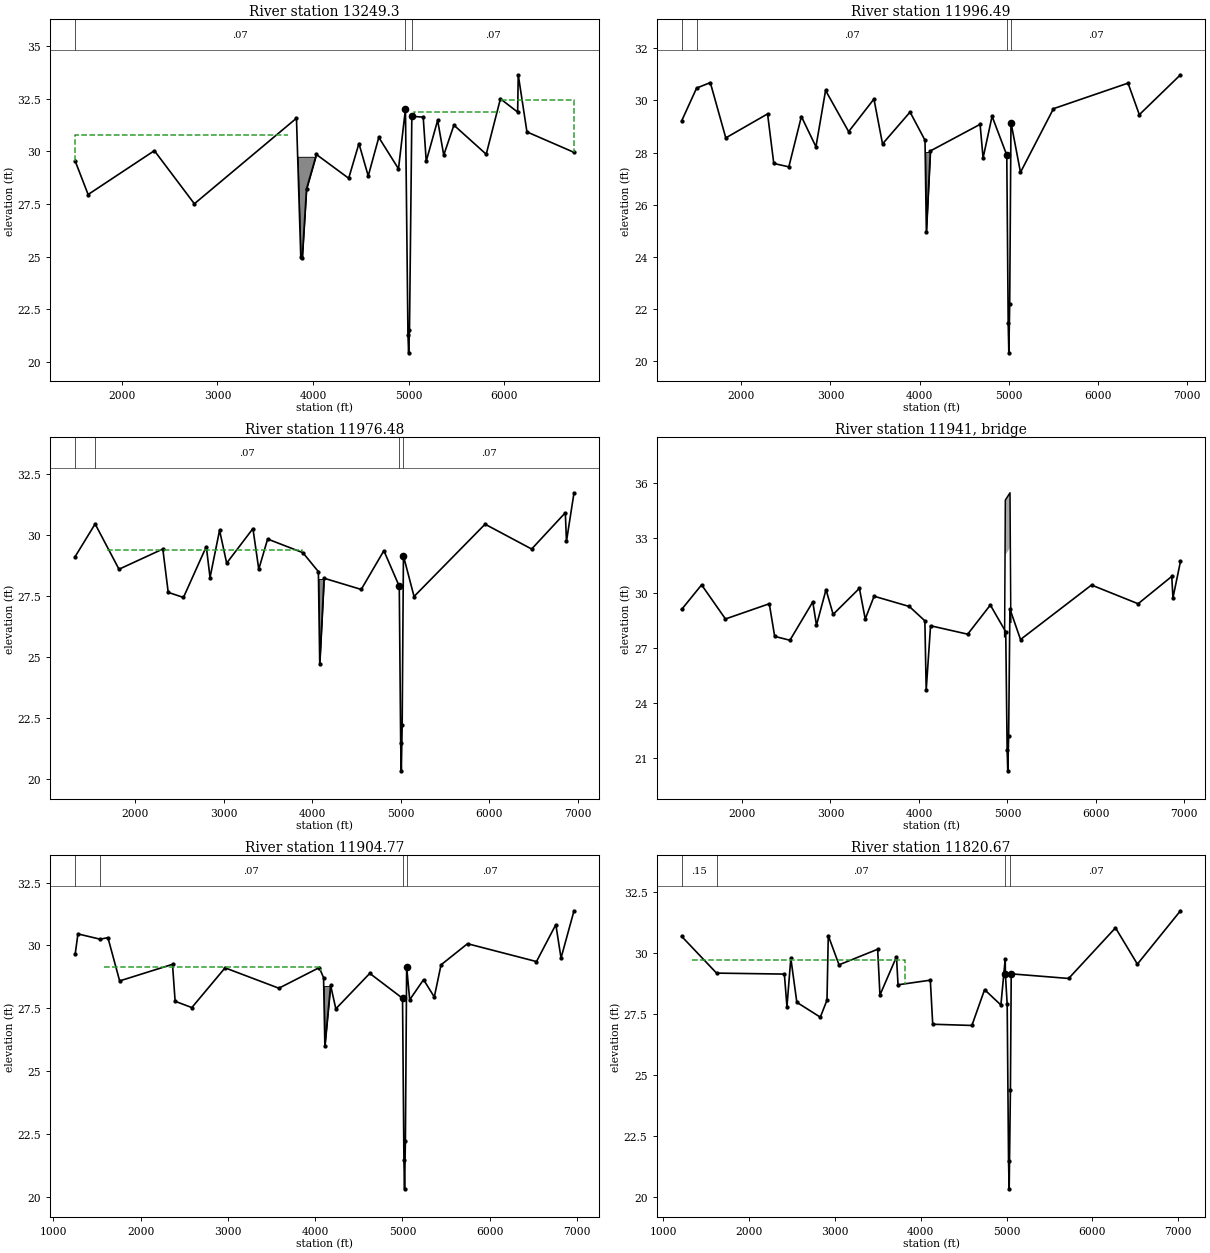
Type RM Length L Ch R = 1 ,13249.3 ,1257.93,1252.81,1245.04
XS GIS Cut Line= 5
     3189220.291    13802287.616     3189347.365    13800399.499
     3189450.888    13798861.313      3189480.36    13798736.489
     3189550.729    13797081.171
#Sta/Elev= 30
 1511.02   29.54 1646.44   27.95 2339.76   30.03 2758.06   27.51 3826.36   31.57
 3871.46      25  3886.5   24.92 3931.68   28.22 4034.82   29.85 4372.68   28.72
 4479.99   30.37 4577.18   28.83 4687.75   30.66 4893.77   29.17 4966.61      32
 4992.83    21.3 4999.95   20.44 5008.89   21.52 5033.39   31.66 5152.39   31.62
 5184.04   29.53  5303.4   31.47 5367.16   29.82  5473.6   31.24 5811.61   29.86
 5960.23   32.49 6140.55   31.86 6146.56   33.63 6237.79   30.92 6730.14   29.95
#Mann= 3 , 0 , 0
 1511.02     .07       0 4966.61    .032       0 5033.39     .07       0
#XS Ineff= 4 ,-1
 1511.02 3737.71   30.79 3737.71 4945.24   30.45 5054.61 5955.63   31.86
 5962.46 6730.14   32.43
Permanent Ineff=
       F       F       F       F
#Block Obstruct= 1 ,-1
 3778.16 4030.72   29.74
Bank Sta=4966.61,5033.39
XS Rating Curve= 0 ,0
Exp/Cntr=0.3,0.1

Type RM Length L Ch R = 1 ,11996.49,20.14,20.01,20.25
XS GIS Cut Line= 5
      3190351.24    13802709.276     3190468.843    13801439.681
     3190687.366    13799080.599     3190695.919     13799034.33
     3190829.373     13797137.82
#Sta/Elev= 30
 1331.34   29.21 1499.11   30.47 1652.79   30.68  1826.3   28.56 2294.76   29.48
 2364.43   27.58 2533.21   27.45 2673.84   29.38 2837.17   28.22 2944.99   30.38
 3203.69    28.8 3487.31   30.05 3583.51   28.33 3892.06   29.55 4059.75   28.47
 4074.81   24.96    4120   28.06 4677.38   29.08 4710.71   27.79 4811.74   29.39
 4976.47    27.9 4992.38   21.45 4999.61   20.32 5009.22   22.21 5023.53   29.15
 5130.19   27.24 5499.91   29.68 6335.91   30.66 6462.44   29.45  6923.8   30.98
#Mann= 4 ,-1 , 0
 1331.34     .15       0 1499.11     .07       0 4976.47    .032       0
 5023.53     .07       0
#XS Ineff= 1 ,-1
 1703.23 3892.61   29.54
Permanent Ineff=
       F
#Block Obstruct= 1 ,-1
 4027.71 4121.25   28.02
Bank Sta=4976.47,5023.53
XS Rating Curve= 0 ,0
Exp/Cntr=0.5,0.3

Type RM Length L Ch R = 1 ,11976.48,56.92,71.71,87.01
XS GIS Cut Line= 5
     3190369.465    13802729.365     3190488.758    13801441.526
     3190707.197    13799083.344     3190715.697    13799037.363
     3190853.651    13797113.542
#Sta/Elev= 30
 1318.94   29.12 1544.43   30.46 1814.22    28.6 2309.47   29.43 2370.38   27.65
 2542.67   27.44 2800.76   29.53 2842.92   28.26 2950.68    30.2 3030.94   28.85
 3327.77   30.27 3393.72    28.6 3493.79   29.84 3892.05   29.28 4067.52    28.5
 4082.59   24.72  4131.9   28.23 4551.32   27.77  4807.4   29.36 4981.47    27.9
 4997.38   21.45 5004.61   20.32 5014.22   22.21 5028.53   29.15 5148.43   27.48
 5950.93   30.45 6477.26   29.43 6857.76   30.92 6871.03   29.75 6956.09   31.74
#Mann= 4 ,-1 , 0
 1318.94     .15       0 1544.43     .07       0 4981.47    .032       0
 5028.53     .07       0
#XS Ineff= 1 ,-1
 1675.52 3882.22   29.41
Permanent Ineff=
       F
#Block Obstruct= 1 ,-1
 4031.18 4128.18    28.2
Bank Sta=4981.47,5028.53
XS Rating Curve= 0 ,0
Exp/Cntr=0.5,0.3

Type RM Length L Ch R = 3 ,11941   ,,,
BEGIN DESCRIPTION:
3' Water Line
END DESCRIPTION:
Bridge Culvert--1,0,-1,-1, 0
Deck Dist Width WeirC Skew NumUp NumDn MinLoCord MaxHiCord MaxSubmerge Is_Ogee
32,3,2.6,0, 4, 4, , , 0.95, 0, 0,0,,
  4968.6 4976.78 5029.86 5038.97
   27.63   35.08   35.48   28.42
   24.63   32.08   32.48   25.42
  4985.6 4993.78 5046.86 5055.97
   27.63   35.08   35.48   28.42
   24.63   32.08   32.48   25.42
Pier Skew, UpSta & Num, DnSta & Num=  ,4981.898, 4 ,4998.898, 4 , 3 , 3 , 0 ,,
     1.2     1.2       2       2
       0   30.25   30.25
     1.2     1.2       2       2
       0   30.25   30.25
Pier Skew, UpSta & Num, DnSta & Num=  ,5021.729, 4 ,5038.729, 4 , 3 , 3 , 0 ,,
     1.2     1.2       2       2
       0   30.25   30.25
     1.2     1.2       2       2
       0   30.25   30.25
BR Coef=-1 , 0 , 0 ,, 0 ,,,0.8,-1,,1,
WSPro=,,,, 1 ,,,, 0 ,,,, 0 ,,,,-1 ,-1 ,-1 , 0 , 0 , 0 , 0 , 0
BC Design=,, 0 ,, 0 ,,,,,,
BC HTab HWMax=31.74
BC Use User HTab Curves=0
BC User HTab FreeFlow(D)= 0

Type RM Length L Ch R = 1 ,11904.77,89.53,84.11,84.5
XS GIS Cut Line= 5
     3190459.874    13802829.021     3190571.381    13801422.592
      3190748.09    13799193.765     3190806.042    13798983.689
     3190926.485     13797137.82
#Sta/Elev= 30
 1251.37   29.65 1282.99   30.46 1537.09   30.25 1626.68   30.31 1761.02   28.59
 2366.38   29.25 2396.47   27.78 2587.82   27.53 2968.58   29.11 3584.83    28.3
 4047.33   29.12 4096.79   28.72 4111.84   26.01 4177.37   28.42 4237.22   27.48
 4626.14   28.89 5001.47    27.9 5017.38   21.45 5024.61   20.32 5034.22   22.21
 5048.53   29.15 5083.54   27.84 5242.29   28.64 5365.41   27.95 5442.55   29.23
 5745.77   30.07 6535.85   29.36 6757.59   30.83 6817.14    29.5 6965.75   31.38
#Mann= 4 ,-1 , 0
 1251.37     .15       0 1537.09     .07       0 5001.47    .032       0
 5048.53     .07       0
#XS Ineff= 1 ,-1
 1585.45 4062.36   29.13
Permanent Ineff=
       F
#Block Obstruct= 1 ,-1
 4076.21 4173.21   28.39
Bank Sta=5001.47,5048.53
XS Rating Curve= 0 ,0
Exp/Cntr=0.5,0.3

Type RM Length L Ch R = 1 ,11820.67,416.76,284.97,396.78
XS GIS Cut Line= 5
     3190533.676     13802910.37     3190651.131    13801428.915
     3190827.237    13799207.689     3190884.465    13799000.236
     3190983.134    13797121.635
#Sta/Elev= 30
 1214.34   30.69 1621.09   29.18 2410.95   29.14 2441.05    27.8 2486.19   29.79
 2556.28   27.98  2829.7   27.37 2907.51   28.07 2922.55   30.72 3047.69   29.52
 3497.71   30.16 3524.44   28.28 3716.95   29.85  3735.1    28.7 4111.27   28.89
 4139.03   27.08 4595.37   27.03 4743.25    28.5 4933.18   27.87 4983.63   29.77
 4985.64   29.13 5006.47    27.9 5022.38   21.45 5029.61   20.32  5044.1   24.36
 5053.53   29.15 5722.33   28.96 6268.13   31.04 6523.06   29.55 7025.03   31.74
#Mann= 4 ,-1 , 0
 1214.34     .15       0 1621.09     .07       0 4983.63    .032       0
  5044.1     .07       0
#XS Ineff= 2 ,-1
 1331.41 3816.97    29.7 6263.94 6940.84   31.01
Permanent Ineff=
       F       F
Bank Sta=4985.64,5053.53
XS Rating Curve= 0 ,0
Exp/Cntr=0.3,0.1

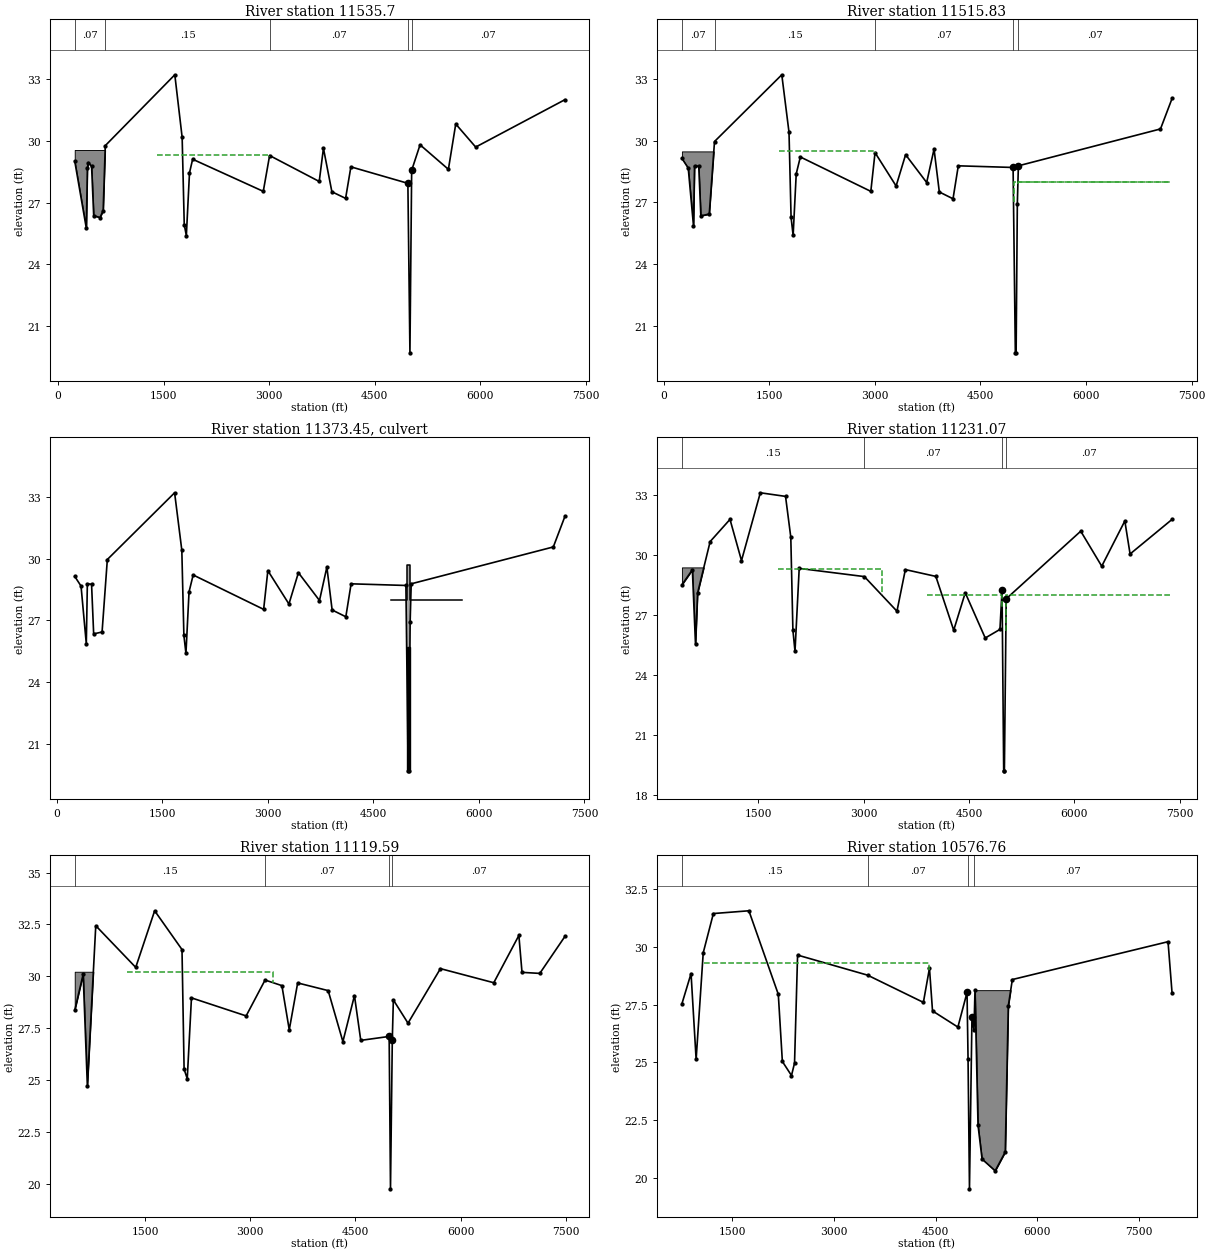
Type RM Length L Ch R = 1 ,11535.7 ,19.87,19.87,19.87
XS GIS Cut Line= 6
  3190789.97752413804054.9845796 3190866.987540613802635.4103191
 3190889.201406913802203.8554079 3191037.194549213799328.7843864
 3191075.6354172 13799291.121404 3191180.282517613797116.9476027
#Sta/Elev= 30
  238.16   29.02  402.77   25.76  417.74   28.67   432.7   28.95   477.6   28.76
  507.53   26.37  597.32   26.28  642.21   26.62  672.14   29.77 1659.82   33.21
 1764.13   30.17 1793.93   25.93 1823.73    25.4 1868.43   28.45 1913.14   29.11
 2916.62   27.55 3006.59   29.29 3711.31   28.03 3771.29   29.64 3891.24   27.53
 4086.16   27.21 4161.13   28.74 4970.81   27.94    5000   19.71 5024.63   28.57
  5143.9   29.81 5546.45   28.62 5650.81   30.82 5934.08    29.7 7201.35      32
#Mann= 5 ,-1 , 0
  238.16     .07       0  672.14     .15       0 3006.59     .07       0
 4970.81    .032       0 5024.63     .07       0
#XS Ineff= 1 ,-1
 1404.16 3002.31   29.33
Permanent Ineff=
       F
#Block Obstruct= 1 ,-1
  238.16     934   29.56
Bank Sta=4970.81,5024.63
XS Rating Curve= 0 ,0
Exp/Cntr=0.3,0.1

Type RM Length L Ch R = 1 ,11515.83,262.27,284.75,347.66
XS GIS Cut Line= 6
 3190802.998167213804054.4639114 3190872.520337913802652.0146166
 3190892.461242913802286.2377891 3191052.719452613799341.1236006
 3191085.335529113799309.5747791 3191203.045595513797114.2953771
#Sta/Elev= 30
     258   29.14  347.63   28.67  422.32   25.87  437.26   28.78  497.01   28.76
  526.88   26.35  646.39   26.44  721.08   29.96 1676.82    33.2 1779.39   30.41
  1808.7   26.28    1838    25.4 1881.96   28.39 1940.57   29.21 2941.78   27.54
 3001.67   29.42 3301.11    27.8 3435.86   29.32 3735.29   27.97  3840.1   29.59
 3914.96   27.51 4109.59   27.18 4184.45   28.78 4962.99    28.7    4995    19.7
    5006    19.7 5023.34   26.95 5038.29   28.78 7057.26   30.57 7221.77   32.05
#Mann= 5 ,-1 , 0
     258     .07       0  721.08     .15       0 3001.67     .07       0
 4962.99    .032       0 5038.29     .07       0
#XS Ineff= 3 ,-1
 1630.48 3006.93   29.49    4969    4969      28    5031 7161.95      28
Permanent Ineff=
       F       F       F
#Block Obstruct= 1 ,-1
     258     826   29.48
Bank Sta=4962.99,5038.29
XS Rating Curve= 0 ,0
Exp/Cntr=0.3,0.1

Type RM Length L Ch R = 2 ,11373.45,,,
BEGIN DESCRIPTION:
New Culvert at Anthony Ln
END DESCRIPTION:
Bridge Culvert--1,0,-1,-1, 0
Deck Dist Width WeirC Skew NumUp NumDn MinLoCord MaxHiCord MaxSubmerge Is_Ogee
15.11,254,2.6,0, 6, 6, , , 0.98, 0, 0,0,,
    4758    4978    4978    5022    5022    5758
      28      28    29.7    29.7      28      28
                                                
    4966    4978    4978    5022    5022    5414
      28      28   31.55   31.55      28      28
                                                
BR Coef=-1 , 0 , 0 ,, 0 ,,,0.8,-1,,0,
WSPro=,,,, 1 ,,,, 0 ,,,, 0 ,,,,-1 ,-1 ,-1 , 0 , 0 , 0 , 0 , 0
Multiple Barrel Culv=2,6,10,254,0.012,0,0,58,1,19.7,19.2, 3,Culvert #1  , 0 ,15.11
    4989    4989    5000    5000    5011    5011
Culvert Bottom n=0.012
BC Design=,, 0 ,, 0 ,,,,,,
BC HTab HWMax=33.2
BC Use User HTab Curves=0
BC User HTab FreeFlow(D)= 0

Type RM Length L Ch R = 1 ,11231.07,111.47,111.47,111.47
XS GIS Cut Line= 5
 3190986.944977813804092.1659357 3191046.777863413803007.6198765
 3191245.550103613799556.8026311 3191303.301956613799489.1882651
 3191413.207904813797145.1001055
#Sta/Elev= 30
     414    28.5  562.79   29.25  607.43   25.52  637.19   28.09  815.74   30.66
 1098.45   31.77 1262.13   29.71 1530.12    33.1 1889.24   32.92 1964.06   30.88
 1993.99   26.24 2023.91   25.17 2083.77   29.32  3011.5   28.91 3475.36   27.18
 3595.07   29.26    4029   28.92 4283.38   26.23 4447.98    28.1 4732.28   25.84
 4941.77   26.27 4971.55   28.23    4995    19.2    5005    19.2 5030.83    27.8
 6091.94   31.18 6390.88   29.43 6719.71   31.69 6794.44   30.04 7392.32   31.77
#Mann= 4 ,-1 , 0
     414     .15       0  3011.5     .07       0 4971.55    .032       0
 5030.83     .07       0
#XS Ineff= 3 ,-1
 1778.29 3256.35   29.31 3905.91    4974  27.991    5026 7377.37      28
Permanent Ineff=
       F       F       F
#Block Obstruct= 1 ,-1
     414     777   29.37
Bank Sta=4971.55,5030.83
XS Rating Curve= 0 ,0
Exp/Cntr=0.3,0.1

Type RM Length L Ch R = 1 ,11119.59,181.27,542.83,640.69
XS GIS Cut Line= 4
 3191092.842075713804086.1498716 3191313.577854713799651.8460762
 3191397.780114113799546.5936621 3191522.529536613797133.0249984
#Sta/Elev= 30
  496.16   28.36  616.15    30.1  676.15   24.72  796.15   32.44 1366.12   30.43
 1636.11   33.16 2026.09   31.29 2056.09   25.52 2101.09   25.06 2161.08   28.96
 2941.05   28.09 3211.04   29.82 3451.03   29.55 3556.02   27.42 3676.02   29.68
    4111   29.31 4320.99   26.85 4485.98   29.07 4575.98   26.91 4980.89    27.1
    5000   19.75 5025.82   26.95  5040.8   28.86 5249.77   27.74 5712.24   30.37
 6473.08   29.69 6831.12   31.97 6875.88   30.19 7129.49   30.14 7487.53   31.92
#Mann= 4 ,-1 , 0
  496.16     .15       0 3211.04     .07       0 4980.89    .032       0
 5025.82     .07       0
#XS Ineff= 1 ,-1
 1242.49 3321.02   30.23
Permanent Ineff=
       F
#Block Obstruct= 1 ,-1
  496.16     850   30.22
Bank Sta=4980.89,5025.82
XS Rating Curve= 0 ,0
Exp/Cntr=0.3,0.1

Type RM Length L Ch R = 1 ,10576.76,1017.89,946.42,888.16
XS GIS Cut Line= 6
  3191302.04342913804128.2508373 3191454.4404339 13800436.103366
 3191735.136066713799993.6678991 3191758.9168591 13799958.064952
  3192339.982298 13799004.401505 3192765.950934213797205.0392901
#Sta/Elev= 30
  759.64   27.54  894.29   28.85  969.09   25.13 1073.81   29.75 1223.42   31.45
 1747.05   31.57 2180.91   27.95 2240.75   25.04 2375.39   24.43 2420.28   24.97
 2465.16   29.65 3497.45   28.78 4320.28    27.6 4410.05   29.08 4454.93   27.23
 4829.19   26.53 4963.93   28.03  4978.9   25.16    5000   19.52  5036.6   26.95
 5066.38    26.4 5081.27   28.13 5125.94   22.28  5185.5   20.81 5379.07    20.3
 5527.97   21.12 5572.64   27.45  5632.2   28.59  7927.9   30.23 7987.55      28
#Mann= 4 ,-1 , 0
  759.64     .15       0 3497.45     .07       0  4978.9    .032       0
 5066.38     .07       0
#XS Ineff= 1 ,-1
 1085.45 4406.47    29.3
Permanent Ineff=
       F
#Block Obstruct= 1 ,-1
 5081.27  5632.2   28.13
Bank Sta=4963.93,5036.6
XS Rating Curve= 0 ,0
Exp/Cntr=0.3,0.1

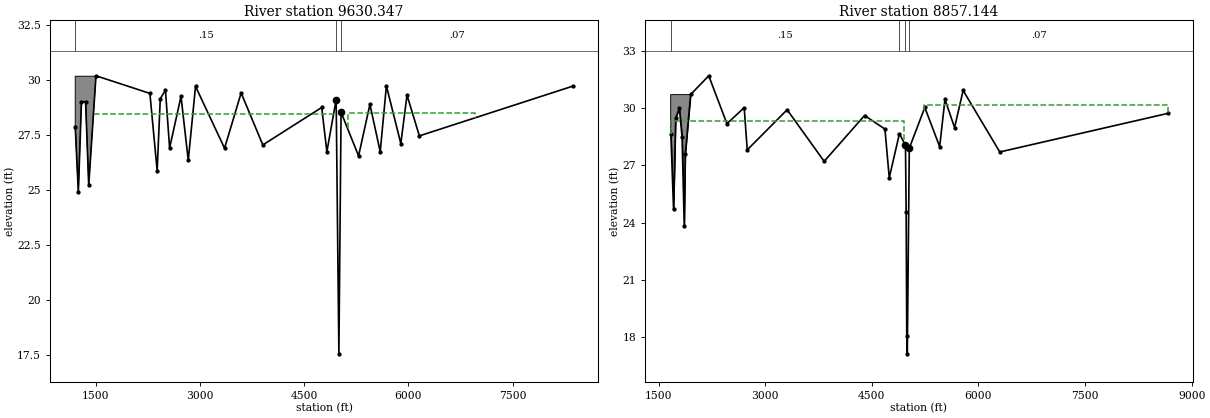
Type RM Length L Ch R = 1 ,9630.347,859.34,773.2,773.2
XS GIS Cut Line= 6
 3191817.147713713804153.0772312 3191974.395430713801799.4260986
 3192534.515045413800502.5320389  3192563.10389913800454.6030009
 3193061.638991113799361.4299904 3193253.779354913797235.1084556
#Sta/Elev= 30
  1204.1   27.88 1248.89   24.91 1293.68   29.01  1353.4   29.01 1398.19   25.22
 1502.69   30.19 2279.04   29.39 2383.55   25.88 2428.34   29.15 2502.99   29.53
 2562.71   26.91 2726.93   29.25 2831.44   26.35 2935.95   29.71 3353.98    26.9
 3592.74   29.41 3905.02   27.05 4752.63   28.75 4826.98   26.74 4960.81   29.11
    5000   17.56 5031.49   28.53 5283.65   26.55 5446.81   28.89 5595.14   26.74
 5684.14   29.73  5891.8   27.11  5980.8   29.31  6158.8   27.46 8367.98   29.72
#Mann= 3 , 0 , 0
  1204.1     .15       0 4960.81    .032       0 5031.49     .07       0
#XS Ineff= 2 ,-1
 1471.13 4921.4828.45524 5124.71 6963.05   28.51
Permanent Ineff=
       F       F
#Block Obstruct= 1 ,-1
  1204.1    1539   30.17
Bank Sta=4960.81,5031.49
XS Rating Curve= 0 ,0
Exp/Cntr=0.3,0.1

Type RM Length L Ch R = 1 ,8857.144,39.17,39.39,37.51
XS GIS Cut Line= 6
     3193031.373    13804200.545     3193083.519    13803142.173
     3193193.714    13800905.629     3193224.075    13800854.956
     3193370.491    13800460.964     3193587.712     13797254.57
#Sta/Elev= 30
 1671.79   28.65 1709.88    24.7 1739.92   29.48 1791.72   29.99 1830.03   28.47
 1860.06   23.85 1875.08    27.6 1950.17   30.71 2205.03   31.69 2460.79   29.18
 2703.63   30.02  2746.6   27.81 3307.91   29.91 3829.13   27.21 4397.12   29.61
 4684.19    28.9 4744.83   26.35 4888.13   28.66 4973.09   28.04 4982.56   24.56
 4991.15   18.09  4998.8   17.13 5026.91    27.9 5244.94   30.03 5454.14   27.98
 5528.74   30.45 5664.05   28.98 5784.32   30.92 6300.17    27.7 8663.83   29.72
#Mann= 4 ,-1 , 0
 1671.79     .15       0 4888.13     .07       0 4973.09    .032       0
 5026.91     .07       0
#XS Ineff= 2 , 0
         4953.81   29.31 5230.95           30.15
Permanent Ineff=
       F       F
#Block Obstruct= 1 ,-1
 1662.54    1960   30.73
Bank Sta=4973.09,5026.91
XS Rating Curve= 0 ,0
Exp/Cntr=0.5,0.3