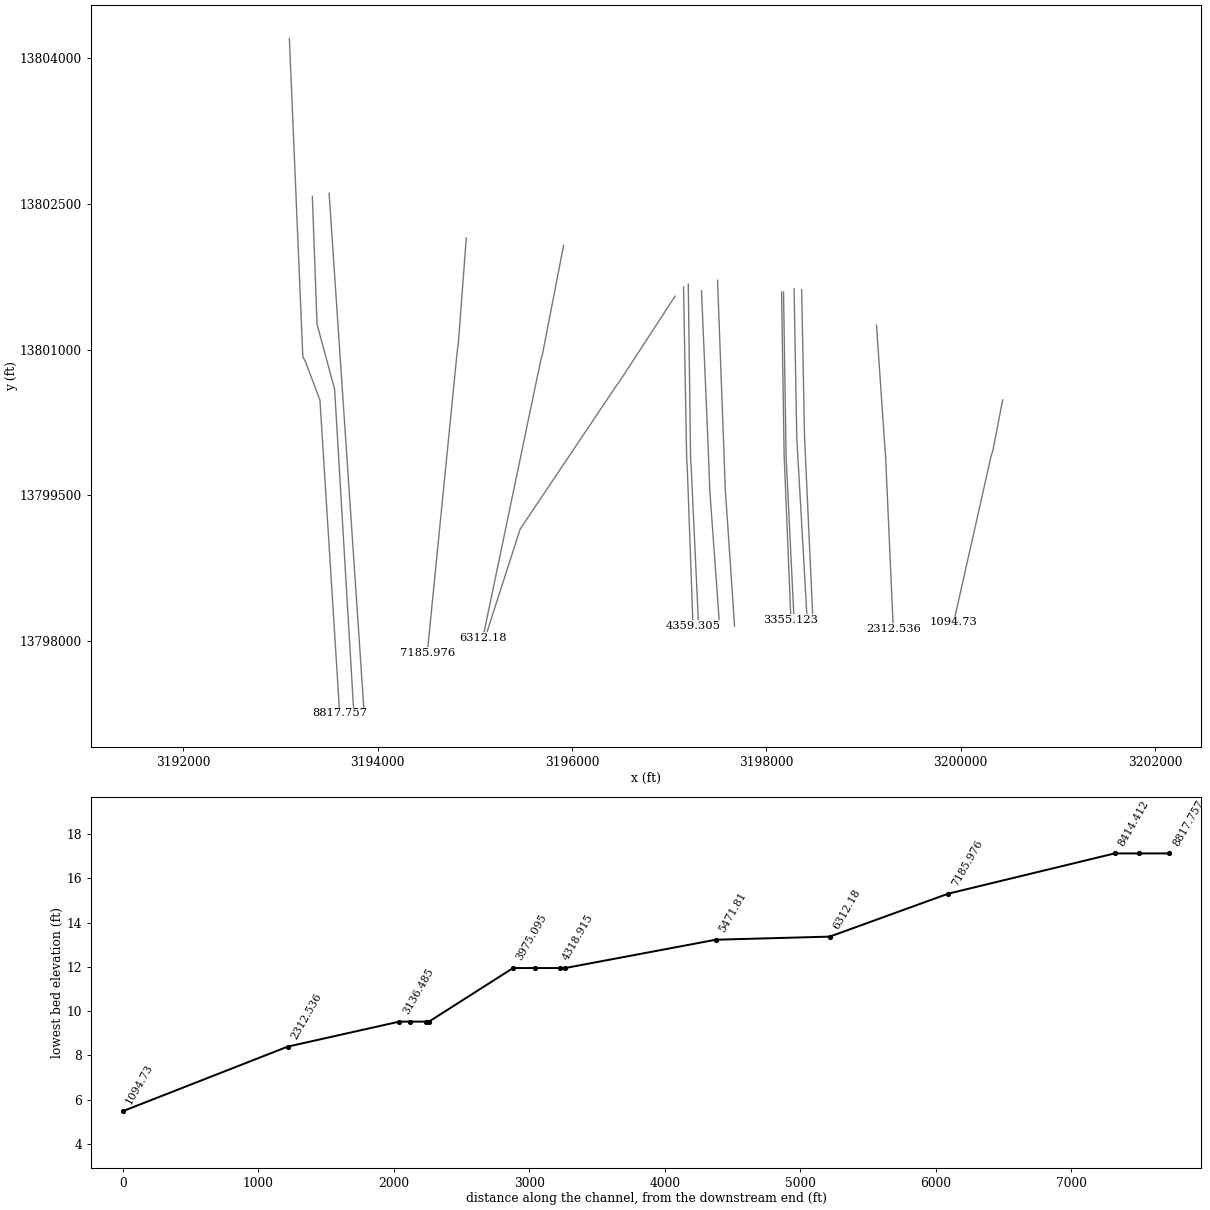
HEC-RAS study B113-00-00.prj: B113-00-00

--- B113-00-00.g01 (geometry) --- (continued)

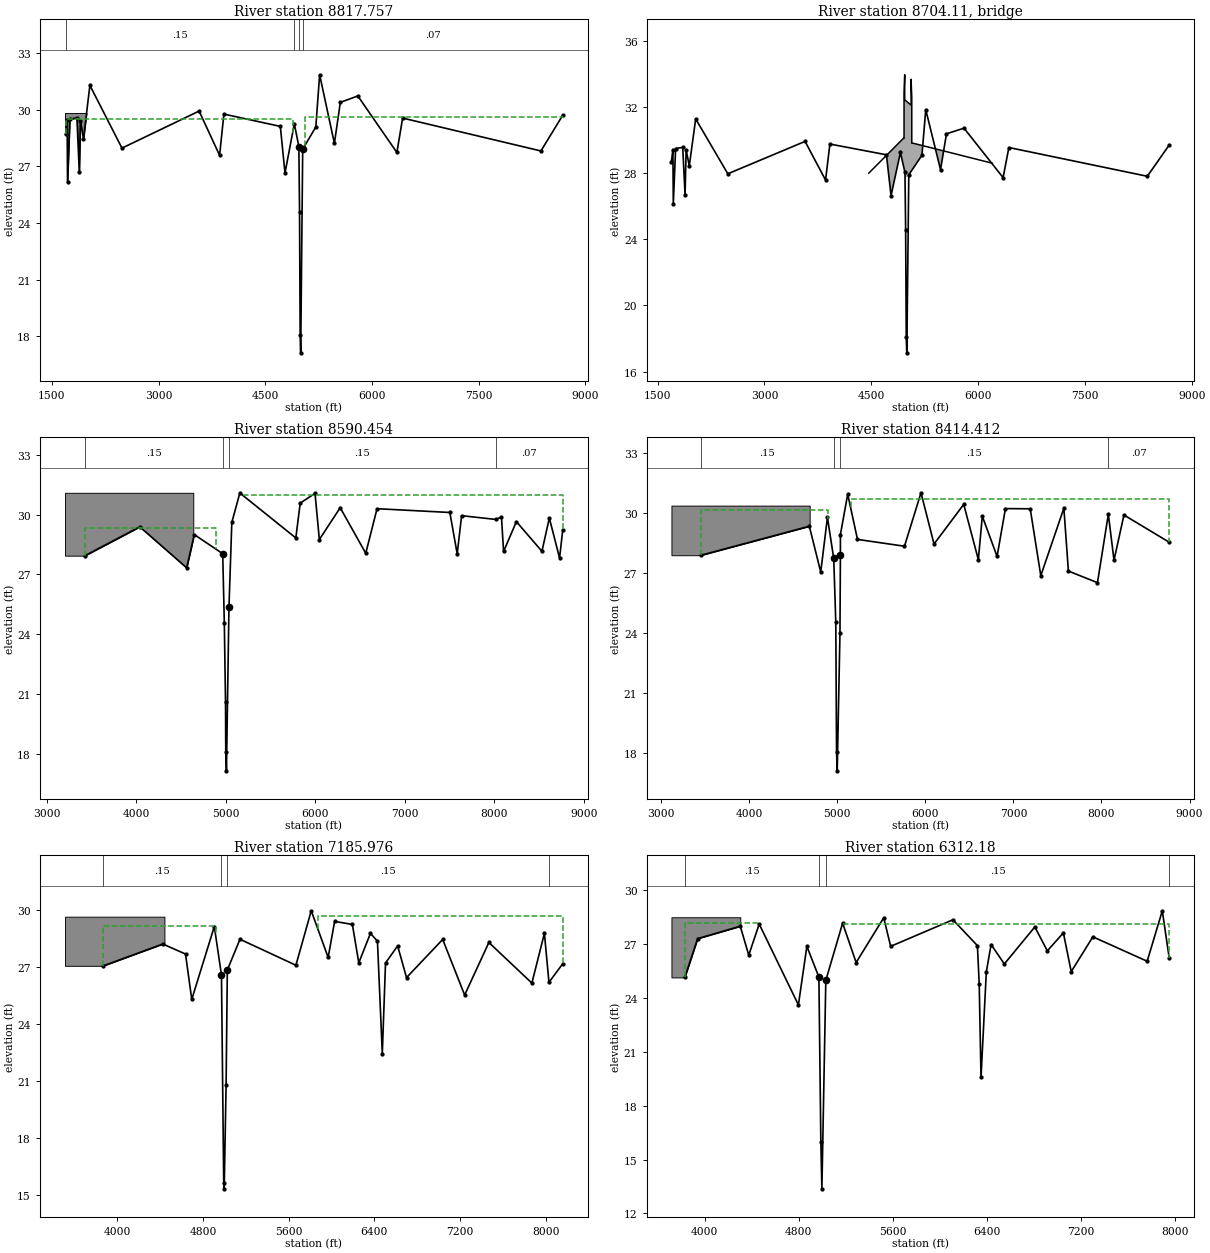
Type RM Length L Ch R = 1 ,8817.757,216.45,227.3,213.06
XS GIS Cut Line= 6
     3193090.105    13804203.659     3193132.131     13803210.23
     3193228.814    13800924.814     3193255.024    13800877.803
     3193404.904    13800480.082     3193607.879    13797255.765
#Sta/Elev= 30
 1693.11    28.7 1713.52   29.43 1719.29   26.16  1751.8   29.49 1851.31   29.56
 1884.44    26.7 1899.45    29.4 1943.59   28.44 2033.58   31.28 2484.98   27.96
 3569.98   29.92 3857.99   27.58 3918.48   29.76 4712.41   29.11 4777.77   26.64
 4909.12   29.25 4973.09   28.04 4982.56   24.56 4991.15   18.09  4998.8   17.13
 5026.91    27.9 5211.46   29.08 5265.07   31.84 5472.76   28.21 5555.93   30.38
 5802.35   30.72 6351.35   27.73 6432.71   29.55  8377.1   27.81 8684.44    29.7
#Mann= 4 ,-1 , 0
 1693.11     .15       0 4909.12     .07       0 4973.09    .032       0
 5026.91     .07       0
#XS Ineff= 2 , 0
         4884.53   29.49 5055.43            29.6
Permanent Ineff=
       F       F
#Block Obstruct= 1 ,-1
  1683.6 2002.31   29.82
Bank Sta=4973.09,5026.91
XS Rating Curve= 0 ,0
Exp/Cntr=0.5,0.3

Type RM Length L Ch R = 3 ,8704.11 ,,,
BEGIN DESCRIPTION:
Jana
END DESCRIPTION:
Bridge Culvert--1,0,-1,-1, 0
Deck Dist Width WeirC Skew NumUp NumDn MinLoCord MaxHiCord MaxSubmerge Is_Ogee
80,106,2.6,0, 12, 12, , , 0.95, 0, 0,0,,
    4465 4950.22 4960.22 4960.22 4969.52 4969.52 5058.97 5058.97 5068.81 5068.81
 5087.81    6200
      28    30.1    30.1   32.83   33.95   32.44   32.11   33.68   32.58   29.81
   29.81    28.6
                                           27.84   27.51
                
    4465 4950.22 4960.22 4960.22 4969.52 4969.52 5058.97 5058.97 5068.81 5068.81
 5087.81    6200
      28    30.1    30.1   32.83   33.95   32.44   32.11   33.68   32.58   29.81
   29.81    28.6
                                           27.84   27.51
                
Pier Skew, UpSta & Num, DnSta & Num=  ,4988.323, 4 ,4998.323, 4 , 3 , 3 , 0 ,,
     1.3     1.3     2.2     2.2
       0   25.73   25.73
     1.3     1.3     2.2     2.2
       0   25.73   25.73
Pier Skew, UpSta & Num, DnSta & Num=  ,5018.18, 4 ,5028.18, 4 , 3 , 3 , 0 ,,
     1.3     1.3     2.2     2.2
       0   25.73   25.73
     1.3     1.3     2.2     2.2
       0   25.73   25.73
BR Coef=-1 , 1 , 0 ,, 0 ,,,0.8,0,2,0,
WSPro=,,,, 1 ,,,, 0 ,,,, 0 ,,,,-1 ,-1 ,-1 , 0 , 0 , 0 , 0 , 0
BC Design=,, 0 ,, 0 ,,,,,,
BC HTab HWMax=31.84
BC Use User HTab Curves=0
BC User HTab FreeFlow(D)= 0

Type RM Length L Ch R = 1 ,8590.454,195.27,176.04,156.34
XS GIS Cut Line= 5
     3193326.577    13802578.279     3193374.983    13801261.153
     3193556.011    13800591.079     3193637.692    13799214.355
     3193753.036    13797270.242
#Sta/Elev= 30
 3427.73   27.94  4040.5   29.39 4564.07   27.33 4649.33      29    4967   28.04
    4985   24.56 4998.48    20.6 5001.15   18.09  5008.8   17.13 5036.91   25.36
 5068.83   29.61 5158.38   31.09 5784.03   28.83 5833.04   30.58  5998.6   31.07
 6046.87   28.75  6279.9   30.35  6565.4   28.06  6691.5    30.3 7504.99   30.11
 7587.19   28.03 7636.46   29.95 8019.09   29.76 8081.81   29.88 8105.35   28.15
 8248.46   29.65 8533.85   28.16 8616.77   29.83 8730.83   27.82 8766.52   29.23
#Mann= 4 ,-1 , 0
 3427.73     .15       0    4967    .032       0 5036.91     .15       0
 8019.09     .07       0
#XS Ineff= 2 ,-1
 3427.73 4890.79   29.34 5191.13 8766.52   30.99
Permanent Ineff=
       F       F
#Block Obstruct= 1 ,-1
 3204.78 4638.23    31.1
Bank Sta=4967,5036.91
XS Rating Curve= 0 ,0
Exp/Cntr=0.5,0.3

Type RM Length L Ch R = 1 ,8414.412,1245.61,1228.44,1210.09
XS GIS Cut Line= 3
     3193499.272    13802608.989     3193710.152    13799481.166
     3193856.884    13797304.804
#Sta/Elev= 30
 3452.98    27.9 4682.07   29.35 4811.57   27.06 4887.72   29.79 4959.12   27.74
 4982.56   24.56 4991.15   18.09  4998.8   17.13    5030      24    5035    27.9
    5035   28.93 5117.86   30.95 5229.12   28.69 5762.57   28.35 5950.39   31.02
 6098.24   28.46 6435.71   30.44  6601.6   27.68  6646.7   29.85 6814.45   27.84
 6909.25   30.23 7190.91   30.22 7310.86   26.88 7573.02   30.25 7624.39   27.11
 7954.66   26.53  8078.1   29.95  8142.3   27.65 8255.35   29.91 8769.21   28.55
#Mann= 4 ,-1 , 0
 3452.98     .15       0 4959.12    .032       0    5035     .15       0
  8078.1     .07       0
#XS Ineff= 2 ,-1
 3452.98 4890.79   30.15 5150.17 8769.21   30.69
Permanent Ineff=
       F       F
#Block Obstruct= 1 ,-1
 3116.04 4686.01   30.38
Bank Sta=4959.12,5035
XS Rating Curve= 0 ,0
Exp/Cntr=0.3,0.1

Type RM Length L Ch R = 1 ,7185.976,886.07,873.8,862.61
XS GIS Cut Line= 5
     3194911.316    13802150.497     3194828.435    13801051.148
     3194819.485    13800997.083     3194655.466    13799346.121
     3194509.936    13797881.261
#Sta/Elev= 30
    3870   27.06 4424.57   28.21 4637.03   27.68 4695.33   25.29 4905.93   29.13
  4972.6   26.58 4993.65   15.61 4998.17   15.31 5015.86   20.77  5027.4   26.84
 5145.32   28.46 5667.51   27.09 5810.69   29.96 5968.57    27.5 6029.05    29.4
 6194.62   29.24 6254.43   27.22  6363.3   28.77 6428.72   28.36 6473.94   22.44
 6504.09   27.21 6617.24   28.11 6700.05   26.44 7037.78   28.45 7242.71   25.52
 7468.81   28.29 7870.32   26.15 7987.22   28.77 8029.78   26.19 8158.43   27.17
#Mann= 4 ,-1 , 0
    3870     .15       0  4972.6    .032       0  5027.4     .15       0
 8029.78     .07       0
#XS Ineff= 2 ,-1
    3870 4918.09   29.16 5873.72 8158.43   29.67
Permanent Ineff=
       F       F
#Block Obstruct= 1 ,-1
 3511.95 4440.27   29.65
Bank Sta=4972.6,5027.4
XS Rating Curve= 0 ,0
Exp/Cntr=0.3,0.1

Type RM Length L Ch R = 1 ,6312.18 ,876.86,840.37,801.4
XS GIS Cut Line= 5
     3195912.715    13802072.718     3195695.652    13800953.141
     3195678.994    13800896.476     3195311.399    13799133.908
     3195082.116    13798034.529
#Sta/Elev= 30
 3829.07   25.14 3938.15    27.3 4301.44   27.99 4373.59   26.38  4462.4   28.11
 4796.18   23.61 4868.16   26.87 4970.47   25.16 4987.17   15.99 4996.05   13.37
 5029.53   24.98 5172.49   28.16 5287.57   25.97 5522.23   28.46 5581.44   26.87
 6111.45   28.35 6319.73   26.91 6335.05   24.77 6350.38   19.57 6395.52   25.44
 6436.27   26.97 6548.87   25.89  6808.4   27.95 6914.87   26.62 7051.44   27.62
  7118.1   25.46 7302.34    27.4 7764.53   26.04 7893.45   28.85 7952.08   26.22
#Mann= 4 ,-1 , 0
 3829.07     .15       0 4970.47    .032       0 5029.53     .15       0
 7952.08     .07       0
#XS Ineff= 2 ,-1
 3829.07 4461.89   28.15 5172.92 7952.08   28.12
Permanent Ineff=
       F       F
#Block Obstruct= 1 ,-1
 3715.53 4301.42   28.49
Bank Sta=4970.47,5029.53
XS Rating Curve= 0 ,0
Exp/Cntr=0.3,0.1

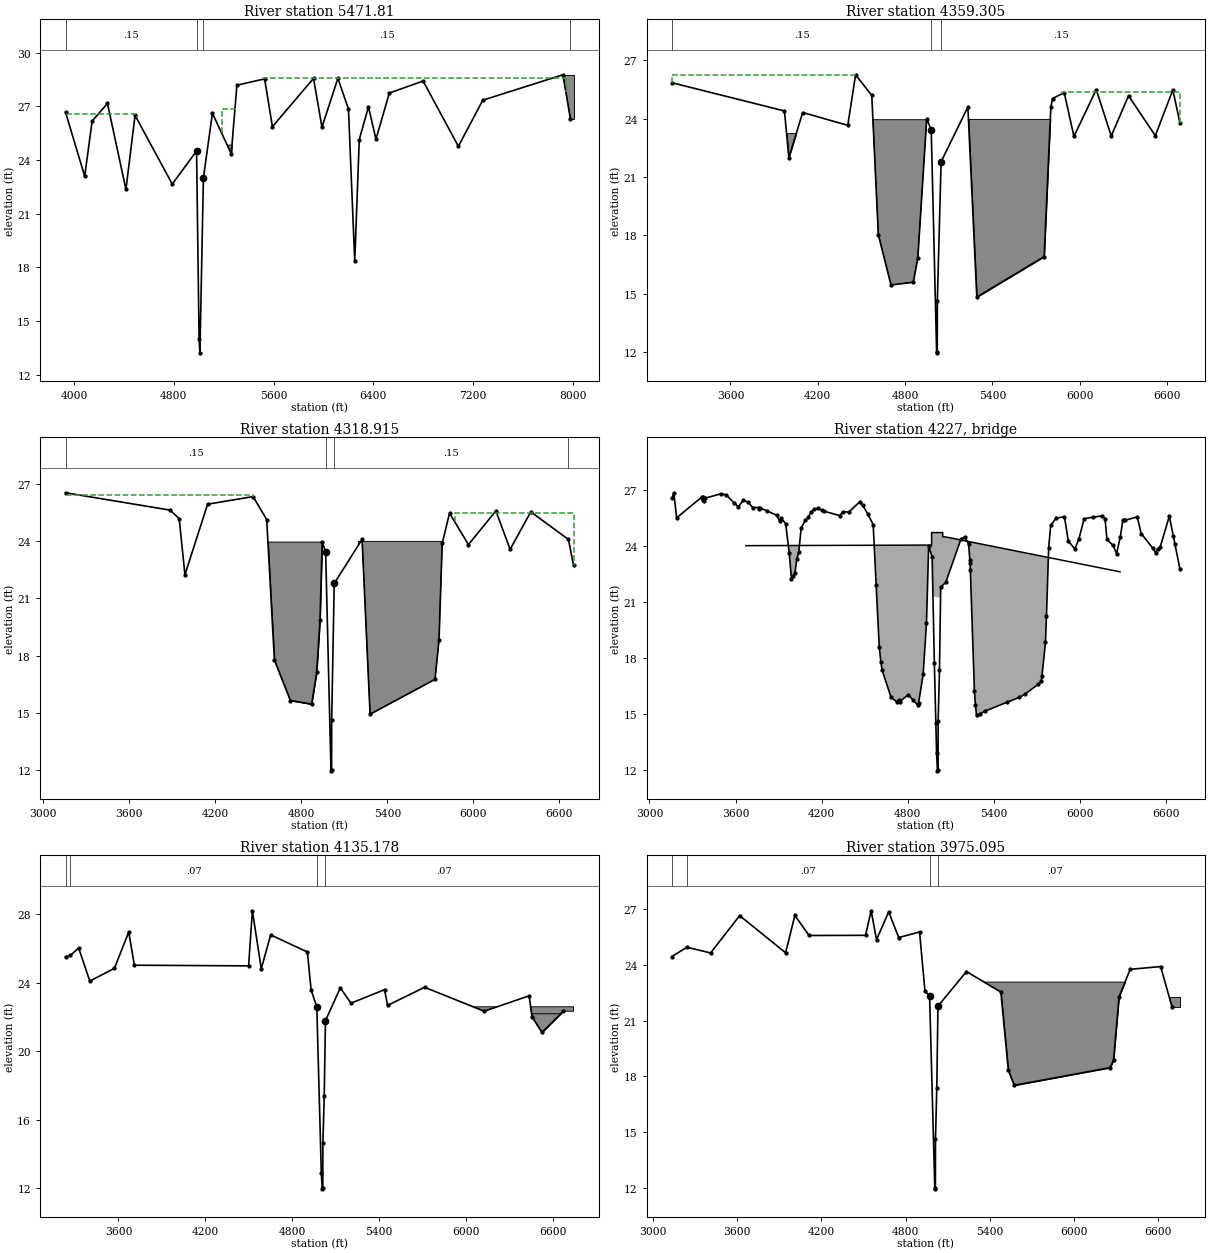
Type RM Length L Ch R = 1 ,5471.81 ,1029.59,1112.5,1178.23
XS GIS Cut Line= 6
 3197059.653298913801549.3412787     3197001.615    13801460.212
     3196490.937    13800675.965     3196458.331    13800631.792
     3195465.736      13799153.2     3195107.148    13798039.994
#Sta/Elev= 30
    3932   26.68 4085.81    23.1 4145.47   26.18 4268.33   27.17 4416.44   22.36
 4489.46    26.5 4787.96   22.66 4982.55   24.51 5002.84   14.03 5009.41   13.23
 5037.45      23 5109.71   26.62  5260.5   24.36 5306.15   28.19 5528.11   28.54
 5590.69   25.87 5920.45   28.57 5987.78   25.84 6115.68   28.57 6200.27   26.86
 6250.77   18.35  6286.9   25.15 6360.47   26.98 6421.08   25.17 6527.74   27.75
 6798.69   28.42 7081.46   24.77 7277.15   27.35 7919.45   28.77 7979.52   26.31
#Mann= 4 ,-1 , 0
    3932     .15       0 4982.55    .032       0 5037.45     .15       0
 7979.52     .07       0
#XS Ineff= 3 ,-1
    3932 4501.71   26.57  5184.3 5309.44   26.84 5514.22 7943.12   28.59
Permanent Ineff=
       F       F       F
#Block Obstruct= 2 ,-1
  5184.3 5309.44   24.87 7919.02 8004.74   28.76
Bank Sta=4982.55,5037.45
XS Rating Curve= 0 ,0
Exp/Cntr=0.3,0.1

Type RM Length L Ch R = 1 ,4359.305,54.74,40.39,41.19
XS GIS Cut Line= 4
      3197147.45    13801644.936     3197179.698    13799862.697
     3197185.149    13799803.465     3197244.673    13798154.622
#Sta/Elev= 30
 3198.16   25.84 3971.23   24.39 4001.44   21.99 4096.75   24.31 4406.62   23.65
 4460.15   26.25 4571.53   25.19 4616.54   18.03 4703.62   15.44 4857.13   15.58
 4887.96   16.84 4949.08   23.99 4980.15   23.41  5017.3   11.95 5021.56   12.01
 5022.12   14.61    5048   21.78 5231.98   24.59 5293.39   14.82 5756.23    16.9
 5802.35   24.58 5814.14   25.03 5894.27   25.33 5960.89   23.08 6114.41   25.49
 6217.23    23.1 6336.24   25.17  6520.5   23.12  6640.7   25.47 6690.09   23.76
#Mann= 3 ,-1 , 0
 3198.16     .15       0 4980.15    .032       0    5048     .15       0
#XS Ineff= 2 ,-1
 3198.16 4460.75   26.25 5880.55 6690.09   25.34
Permanent Ineff=
       F       F
#Block Obstruct= 4 ,-1
 3937.43  4078.5   23.25 4452.09 4956.28   23.94 5216.29  5841.5   23.98
 6176.34 6276.45   23.25
Bank Sta=4980.15,5048
XS Rating Curve= 0 ,0
Exp/Cntr=0.5,0.3

Type RM Length L Ch R = 1 ,4318.915,185.23,183.74,182.23
XS GIS Cut Line= 4
     3197196.062    13801674.103     3197219.912    13799862.215
     3197225.382    13799802.775     3197303.007    13798135.177
#Sta/Elev= 30
 3156.84   26.54 3886.19   25.63 3949.33   25.18 3989.23   22.24 4147.26   25.94
 4464.39   26.34 4559.28   25.13 4612.86   17.76 4724.22   15.64  4872.3   15.45
 4907.61   17.11  4930.8   19.86 4945.97   23.97 4970.15   23.41  5007.3   11.95
 5011.56   12.01 5012.12   14.61 5029.85   21.78 5224.05    24.1 5279.84   14.92
 5732.46   16.75 5760.36   18.83 5782.45   23.88 5833.63   25.47 5965.39   23.82
 6156.63   25.59 6255.89   23.57 6399.91   25.54 6662.57   24.09 6697.98   22.73
#Mann= 4 ,-1 , 0
 3156.84     .15       0 4970.15    .032       0 5029.85     .15       0
 6662.57     .07       0
#XS Ineff= 2 ,-1
 3156.84  4465.3   26.41 5871.44 6697.98   25.46
Permanent Ineff=
       F       F
#Block Obstruct= 2 ,-1
 4445.38 4949.58   23.98 5198.32 5803.37   23.99
Bank Sta=4970.15,5029.85
XS Rating Curve= 0 ,0
Exp/Cntr=0.5,0.3

Type RM Length L Ch R = 3 ,4227    ,,,
BEGIN DESCRIPTION:
Holly Bay Court @ Crenshaw Road
END DESCRIPTION:
Bridge Culvert--1,0,-1,-1, 0
Deck Dist Width WeirC Skew NumUp NumDn MinLoCord MaxHiCord MaxSubmerge Is_Ogee
103,43,2.6,0, 10, 10, , , 0.95, 0, 0,0,,
    3672 4935.49 4966.58 4966.58 4976.39 5034.13 5043.96 5043.96 5062.46    6280
      24   24.03   24.03    24.7    24.7    24.7    24.7   24.47   24.47    22.6
                                    21.3   21.18
    3672 4935.49 4966.58 4966.58 4976.39 5034.13 5043.96 5043.96 5062.46    6280
      24   24.03   24.03    24.7    24.7    24.7    24.7   24.47   24.47    22.6
                                    21.3   21.18
BR Coef=-1 , 0 , 0 ,, 0 ,,,0.8,0,,1,
WSPro=,,,, 1 ,,,, 0 ,,,, 0 ,,,,-1 ,-1 ,-1 , 0 , 0 , 0 , 0 , 0
BR U #Sta/Elev= 117
 3156.84   26.54 3169.57   26.83 3189.56   25.49  3362.8   26.59 3366.35   26.54
 3372.24   26.59 3375.03   26.42 3379.64   26.37 3385.54   26.54 3496.52   26.77
 3534.95   26.72 3592.22   26.27 3619.89   26.08 3652.39   26.42  3686.1   26.34
  3719.2   26.04 3761.59   26.04 3764.21   25.98 3768.02   26.03 3816.24   25.87
 3886.19   25.63 3907.08   25.32 3919.04   25.46 3949.33   25.18  3974.4   23.59
 3989.23   22.24 4003.67   22.38    4014   22.55 4027.17   23.28 4040.63   23.66
 4057.69   24.96 4086.32   25.35 4107.31   25.52 4125.63    25.8 4147.26   25.94
 4172.02      26  4203.8   25.89 4213.91   25.85  4325.5   25.61 4349.26   25.82
 4388.63   25.79 4464.39   26.34 4485.04   26.18 4521.14    25.7 4559.28   25.13
 4579.84   21.91 4601.47   18.59 4612.86   17.76  4621.8   17.33 4684.05   15.88
 4724.22   15.64 4739.29   15.75 4746.18   15.66 4803.21   16.02    4836   15.75
  4872.3   15.45 4875.78   15.58 4907.61   17.11  4930.8   19.86 4945.97   23.97
 4970.15   23.41 4985.74    17.7 4996.16   14.49 5001.21    12.9  5007.3   11.95
 5011.56   12.01 5012.12   14.61  5021.3   17.35 5029.85   21.78 5065.02   22.03
 5170.94   24.35 5196.64   24.46 5224.05    24.1 5233.03   23.25 5234.79   23.08
 5236.39   22.72 5264.82   16.23 5272.31   15.45 5279.84   14.92 5306.24   15.01
 5339.76   15.15 5495.47   15.63 5576.98   15.88 5615.31   16.04 5711.27   16.59
 5732.46   16.75 5735.91   17.04 5760.36   18.83 5767.28   20.25 5782.45   23.88
 5796.51   25.08 5833.63   25.47 5892.28   25.55 5919.51   24.24 5965.39   23.82
 5994.02   24.38 6029.49   25.44 6093.31   25.53 6156.63   25.59 6175.31   25.44
  6188.9   24.33 6231.42   24.01 6255.89   23.57 6281.41   24.46 6299.59   25.35
 6305.27   25.37 6315.25   25.36 6399.91   25.54  6427.3   24.65 6506.86   23.88
 6527.74   23.63 6544.76   23.84  6559.9   23.93 6623.31   25.57    6652    24.5
 6662.57   24.09 6697.98   22.73
BR U #Mann= 4
 3156.84     .15 4970.15    .015 5029.85     .15 6662.57     .07
BR D #Sta/Elev= 129
 3234.93    25.5 3255.16    25.5  3269.3   25.59 3276.23   25.63 3325.46   26.03
 3399.06   24.15  3402.8   24.09 3493.53   24.56 3573.01   24.84 3623.79   26.07
 3639.56   26.04 3643.09   25.87 3666.56   26.82 3671.53   26.96 3685.35    26.6
  3710.3   25.02  3721.7   25.13 3841.53   25.64 3886.45   25.41 3905.46   24.96
 3960.82   25.39 3993.56   25.42 3999.89   25.54 4095.44   25.72 4104.98   25.62
 4107.93   25.68 4132.69   25.45 4231.09    24.8 4293.89   25.46 4351.27   25.73
  4364.1   25.68 4499.22   24.98 4521.72   27.64 4525.36    28.2 4542.47   27.59
 4586.65   24.81 4651.51   26.79 4660.49   26.61 4742.54   26.13 4756.85   26.51
 4771.13   26.16 4807.46   25.85 4838.58   25.71 4840.33   25.63 4867.05   25.58
 4882.88   25.55 4905.18   25.79 4926.06   24.03 4930.72   23.57 4933.31   23.58
 4945.97   23.18 4970.15   22.59 4985.74    17.7 4996.16   14.49 5001.21    12.9
  5007.3   11.95 5011.56   12.01 5012.12   14.61  5021.3   17.35 5029.85   21.78
 5065.02   22.03 5093.94   23.07 5132.57   23.69 5154.87   23.48 5178.57   23.63
 5206.31    22.8 5239.97   22.82 5268.49   23.11 5288.82   23.11 5316.72   23.12
 5376.29   23.31 5437.59   23.59 5455.15   22.68 5458.61   22.67 5496.67   23.38
 5518.66   22.78 5570.82   23.46 5579.98    23.4 5587.32   23.32 5631.72   22.95
 5648.35   22.89 5711.07   23.73 5711.55   23.72 5714.51   23.73 5759.41   23.49
 5772.21   23.41 5815.34   23.03 5832.37   23.08 5842.18   23.06 5847.41   23.07
 5872.73   23.49 5877.89   23.44 5880.24   23.38  5883.8   23.47  5925.3   23.31
 5956.35   22.84 5982.76    23.2 5992.14   23.12 6027.88   22.87 6048.53   22.67
 6096.19   22.38 6103.07   22.56 6118.45   22.39 6126.08   22.33 6156.98   22.74
 6162.07   23.06 6165.73   23.08 6225.08   22.93    6294   23.22 6310.93   22.79
 6334.99   22.71 6373.78    22.4 6408.25   22.99 6436.38   23.23 6455.99   22.01
 6464.01   22.08 6475.08   21.62 6485.48   21.55 6523.71    21.1 6524.56   21.09
 6556.13   21.53 6569.28   21.43 6580.66    21.4 6609.76   21.28 6618.72   21.27
  6635.1   22.03 6662.26   22.26 6670.69   22.27 6672.27   22.33
BR D #Mann= 4
 3234.93     .15  3269.3     .07 4970.15    .015 5029.85     .07
BC Design=,, 0 ,, 0 ,,,,,,
BC HTab HWMax=26.83
BC Use User HTab Curves=0
BC User HTab FreeFlow(D)= 0

Type RM Length L Ch R = 1 ,4135.178,160.08,160.08,160.08
XS GIS Cut Line= 4
     3197332.174    13801606.046     3197401.824    13799975.416
     3197417.191    13799553.918     3197516.899    13798174.066
#Sta/Elev= 30
 3234.93    25.5  3269.3   25.59 3325.46   26.03  3402.8   24.09 3573.01   24.84
 3671.53   26.96  3710.3   25.02 4499.22   24.98 4525.36    28.2 4586.65   24.81
 4651.51   26.79 4905.18   25.79 4930.72   23.57 4970.15   22.59 5001.21    12.9
  5007.3   11.95 5011.56   12.01 5012.12   14.61  5021.3   17.35 5029.85   21.78
 5132.57   23.69 5206.31    22.8 5437.59   23.59 5458.61   22.67 5714.51   23.73
 6126.08   22.33 6436.38   23.23 6455.99   22.01 6524.56   21.09 6672.27   22.33
#Mann= 4 ,-1 , 0
 3234.93     .15       0  3269.3     .07       0 4970.15    .032       0
 5029.85     .07       0
#Block Obstruct= 2 ,-1
 5130.16 6742.94   22.59 6431.17 6672.26   22.21
Bank Sta=4970.15,5029.85
XS Rating Curve= 0 ,0
Exp/Cntr=0.5,0.3

Type RM Length L Ch R = 1 ,3975.095,621.08,619.97,624.11
XS GIS Cut Line= 4
     3197497.454    13801712.992     3197562.145    13799969.521
     3197576.988    13799562.381     3197672.456    13798154.622
#Sta/Elev= 30
 3134.73   24.45 3241.62   24.95 3409.83   24.64 3616.97   26.65 3944.41   24.65
 4010.37   26.66 4111.61   25.58 4513.83   25.59 4553.62   26.91 4591.94   25.36
 4679.04   26.85 4750.33   25.47 4898.62   25.77 4937.17   22.59 4970.15   22.33
  5007.3   11.95 5011.56   12.01 5012.12   14.61  5021.3   17.35 5029.85   21.78
 5232.83   23.64 5477.84   22.54 5530.87   18.34 5573.25   17.52 6255.73   18.47
 6280.74   18.86 6319.77   22.28 6399.12   23.76 6616.17   23.91  6697.8   21.72
#Mann= 4 ,-1 , 0
 3134.73     .15       0 3241.62     .07       0 4970.15    .032       0
 5029.85     .07       0
#Block Obstruct= 2 ,-1
 5290.58 6574.64    23.1 6608.65 6754.27   22.27
Bank Sta=4970.15,5029.85
XS Rating Curve= 0 ,0
Exp/Cntr=0.3,0.1

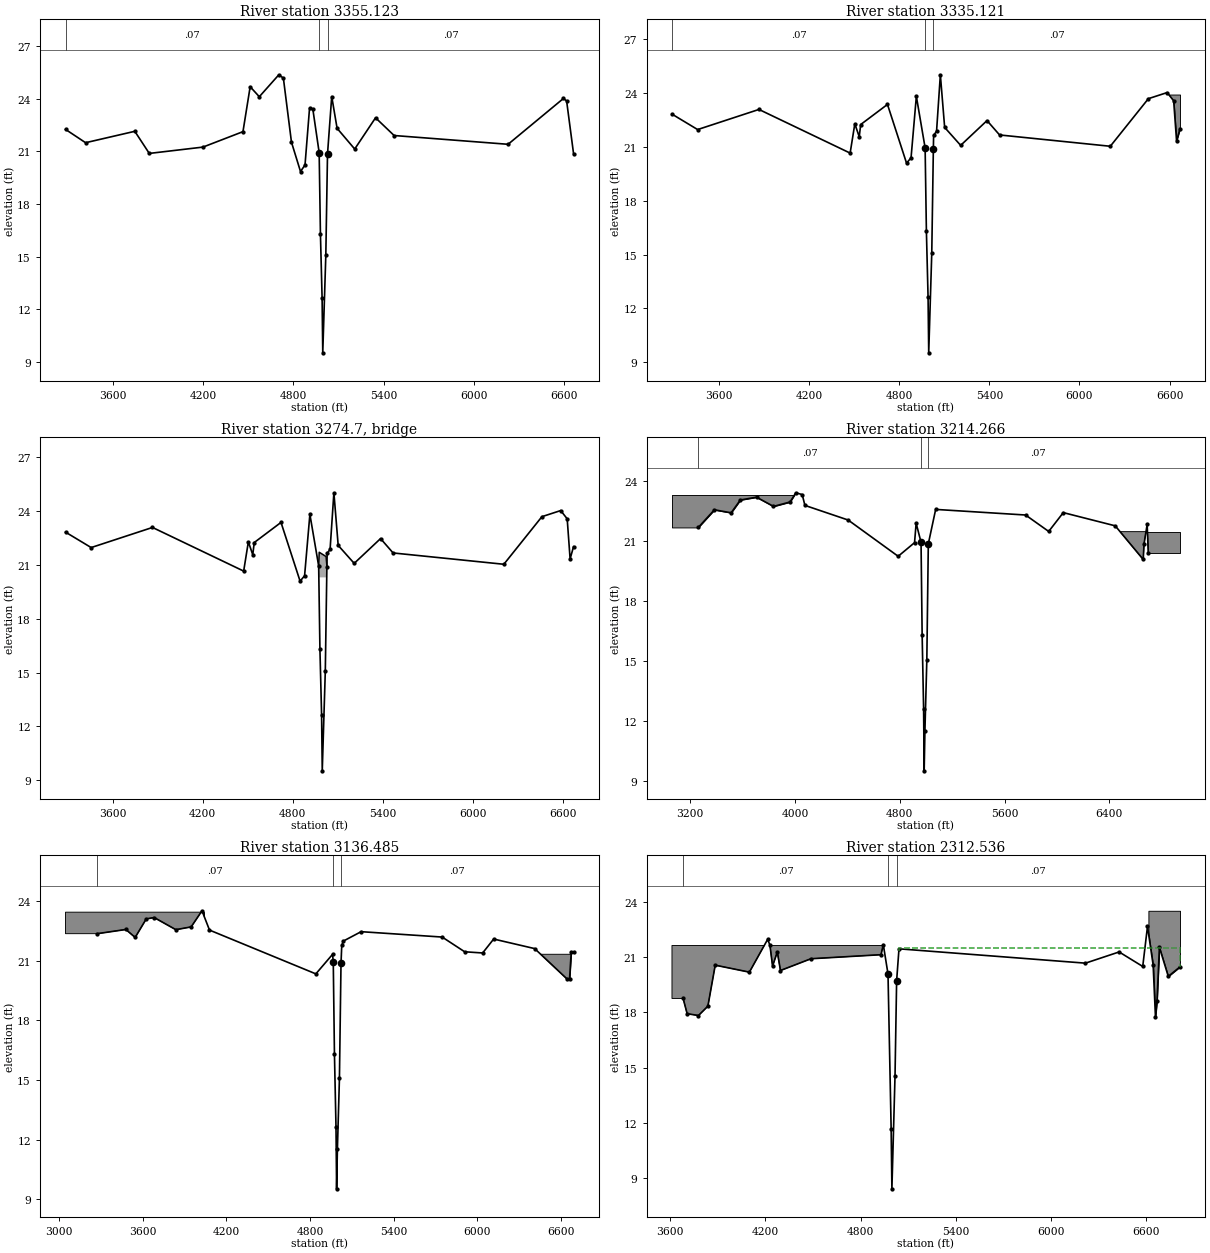
Type RM Length L Ch R = 1 ,3355.123,20.02,20,20.62
XS GIS Cut Line= 4
     3198156.244    13801593.172     3198182.847    13799907.803
     3198185.192    13799851.519     3198252.538    13798218.787
#Sta/Elev= 30
 3286.67   22.26 3420.14    21.5 3747.18   22.15 3843.36   20.89 4199.94   21.25
 4465.94   22.13 4513.73   24.69 4574.52   24.12 4704.29   25.37 4734.46   25.18
 4788.24   21.53 4848.25   19.86 4878.25   20.23 4908.26   23.46 4929.96   23.43
 4972.23   20.94 4980.68   16.31 4991.81   12.63 4996.16    9.53 5016.45   15.08
 5027.77   20.86 5055.75   24.13 5091.44   22.32 5208.47   21.14 5346.92   22.92
 5470.35   21.91 6227.69   21.41  6595.4   24.02 6616.66   23.88  6662.7   20.88
#Mann= 3 ,-1 , 0
 3286.67     .07       0 4972.23    .032       0 5027.77     .07       0
Bank Sta=4972.23,5027.77
XS Rating Curve= 0 ,0
Exp/Cntr=0.5,0.3

Type RM Length L Ch R = 1 ,3335.121,117.73,120.86,121.81
XS GIS Cut Line= 4
     3198176.241    13801593.488     3198202.841    13799908.377
     3198205.153     13799852.88     3198284.962    13798212.956
#Sta/Elev= 30
 3286.65   22.82  3457.5   21.96 3865.79   23.08 4472.94   20.65  4504.1   22.28
 4533.51   21.56 4543.32   22.24 4721.52   23.36 4848.55   20.09 4878.55   20.39
 4913.83   23.81 4972.23   20.94 4980.68   16.31 4991.81   12.63 4996.16    9.53
 5016.45   15.08    5027   20.86 5028.76   21.63  5048.4   21.87 5073.66   25.01
 5102.27   22.08 5208.82   21.08 5384.36   22.46 5467.89   21.66 6205.21   21.03
 6458.78   23.68 6583.79   24.02 6627.07   23.56 6646.46   21.33 6669.38   22.01
#Mann= 3 ,-1 , 0
 3286.65     .07       0 4972.23    .032       0    5027     .07       0
#Block Obstruct= 1 ,-1
 6567.69 6669.38   23.91
Bank Sta=4972.23,5027
XS Rating Curve= 0 ,0
Exp/Cntr=0.5,0.3

Type RM Length L Ch R = 3 ,3274.7  ,,,
BEGIN DESCRIPTION:
Wooden Vehicular Bridge
END DESCRIPTION:
Bridge Culvert--1,0,-1,-1, 0
Deck Dist Width WeirC Skew NumUp NumDn MinLoCord MaxHiCord MaxSubmerge Is_Ogee
48,13,2.6,0, 4, 4, , , 0.95, 0, 0,0,,
 4972.23 4975.91 5021.59 5027.77
   20.94    21.7   21.46   20.86
            20.3    20.3
 4962.23 4967.91 5013.59 5017.77
   20.94    21.7   21.46   20.86
            20.3    20.3
Pier Skew, UpSta & Num, DnSta & Num=  ,4990.522, 2 ,4981.522, 2 , 0 , 0 , 0 ,,
       1       1
       0
       1       1
       0
Pier Skew, UpSta & Num, DnSta & Num=  ,5005.688, 2 ,4996.688, 2 , 0 , 0 , 0 ,,
       1       1
       0
       1       1
       0
BR Coef=-1 , 1 , 0 ,, 0 ,,,0.8,0,2,0,
WSPro=,,,, 1 ,,,, 0 ,,,, 0 ,,,,-1 ,-1 ,-1 , 0 , 0 , 0 , 0 , 0
BC Design=,, 0 ,, 0 ,,,,,,
BC HTab HWMax=25.01
BC Use User HTab Curves=0
BC User HTab FreeFlow(D)= 0

Type RM Length L Ch R = 1 ,3214.266,78.91,77.78,76.65
XS GIS Cut Line= 3
     3198284.962    13801625.491     3198312.958    13800089.605
     3198421.075    13798193.511
#Sta/Elev= 30
 3261.73   21.68 3384.44   22.56 3512.35   22.41 3582.57   23.05 3706.18   23.19
 3835.53   22.73 3962.22   22.95 4005.93   23.41 4055.01   23.32 4075.57   22.78
 4405.62   22.05 4787.53   20.24 4912.65   20.92 4924.87   21.89 4962.23   20.94
 4970.68   16.31 4981.81   12.63 4986.16    9.53 4991.85   11.52 5006.45   15.08
 5017.77   20.86 5073.92   22.58 5760.43    22.3 5936.99   21.48 6048.34   22.42
 6444.98   21.76 6658.71   20.08 6665.02   20.86 6688.76   21.83 6697.04   20.42
#Mann= 3 ,-1 , 0
 3261.73     .07       0 4962.23    .032       0 5017.77     .07       0
#Block Obstruct= 2 ,-1
  3060.5  4008.4    23.3 5084.14 6939.61   21.47
Bank Sta=4962.23,5017.77
XS Rating Curve= 0 ,0
Exp/Cntr=0.5,0.3

Type RM Length L Ch R = 1 ,3136.485,820.61,823.95,824.16
XS GIS Cut Line= 3
     3198362.741    13801615.769     3198393.143    13800091.857
     3198479.408    13798203.233
#Sta/Elev= 30
 3275.52   22.35  3479.8   22.56 3546.67   22.16 3626.12   23.09  3682.8   23.16
 3838.38   22.55 3948.21   22.69 4025.86    23.5 4079.66   22.53 4842.35   20.33
    4962   21.31 4967.23   20.94 4975.68   16.31 4986.81   12.63 4991.16    9.53
 4996.85   11.52 5011.45   15.08 5022.77   20.86 5028.12   21.76 5040.06   21.98
  5166.9   22.45 5748.09   22.18 5909.52   21.44 6038.45   21.38 6117.47   22.08
 6411.46    21.6 6645.64   20.06 6661.74   20.07 6673.76   21.43 6690.33   21.42
#Mann= 3 ,-1 , 0
 3275.52     .07       0 4967.23    .032       0 5022.77     .07       0
#Block Obstruct= 2 ,-1
 3047.06 4042.02   23.43 5173.83 7002.37   21.34
Bank Sta=4967.23,5022.77
XS Rating Curve= 0 ,0
Exp/Cntr=0.3,0.1

Type RM Length L Ch R = 1 ,2312.536,1252.26,1217.81,1174.2
XS GIS Cut Line= 4
     3199133.257    13801251.696     3199221.644    13799964.087
     3199226.563       13799910.     3199305.806    13798125.455
#Sta/Elev= 30
 3681.74   18.76 3707.07   17.93 3778.49   17.83 3837.86   18.34 3884.08   20.57
 4099.31   20.19 4214.12   21.97 4228.62   21.67 4245.43   20.52 4275.36   21.29
 4295.17   20.28 4487.44   20.92 4929.03   21.14 4943.24   21.69 4972.84   20.09
 4992.62   11.67  4997.4     8.4 5017.11   14.56 5027.16   19.72 5042.07   21.46
 6217.19   20.68 6429.27   21.29 6578.06    20.5 6608.09   22.68 6643.64   20.58
 6658.38   17.74 6668.15   18.64 6683.17   21.54 6739.02   19.96 6812.99   20.48
#Mann= 3 ,-1 , 0
 3681.74     .07       0 4972.84    .032       0 5027.16     .07       0
#XS Ineff= 1 ,-1
 5040.96 6888.51    21.5
Permanent Ineff=
       F
#Block Obstruct= 2 ,-1
 3611.49 4941.41   21.64 6613.77 6812.99   23.53
Bank Sta=4972.84,5027.16
XS Rating Curve= 0 ,0
Exp/Cntr=0.3,0.1

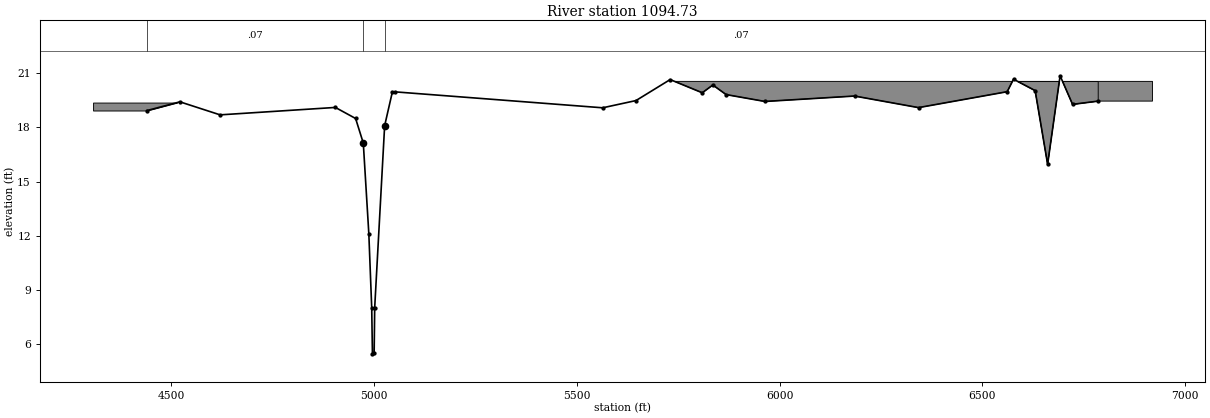
Type RM Length L Ch R = 1 ,1094.73 ,926.4,1094.73,1265.52
XS GIS Cut Line= 4
     3200432.065    13800482.665     3200330.694    13799959.221
     3200314.051    13799909.308     3199928.035    13798193.511
#Sta/Elev= 30
 4440.85   18.93 4521.63   19.41 4620.71   18.69 4904.85    19.1 4954.72   18.49
 4973.69   17.13 4987.31   12.13 4994.45    8.02 4996.18    5.48 5000.42     5.5
  5001.8    8.04 5026.31   18.09 5045.18   19.94 5052.65   19.96 5563.76   19.08
 5645.89   19.48 5730.13   20.64 5809.32   19.91 5835.34   20.34 5868.11   19.81
 5963.81   19.43 6184.67   19.73 6342.42   19.09 6560.99   19.97 6576.54   20.66
 6629.89   20.03 6660.64   15.96 6691.39   20.85 6722.14   19.27 6785.32   19.45
#Mann= 3 ,-1 , 0
 4440.85     .07       0 4973.69    .032       0 5026.31     .07       0
#Block Obstruct= 3 ,-1
 4307.56 4514.29   19.37 5732.79 6919.03   20.54  6580.2 6785.32   20.53
Bank Sta=4973.69,5026.31
XS Rating Curve= 0 ,0
Exp/Cntr=0.3,0.1

Chan Stop Cuts=-1
Use User Specified Reach Order=0
Composite Channel Slope=5